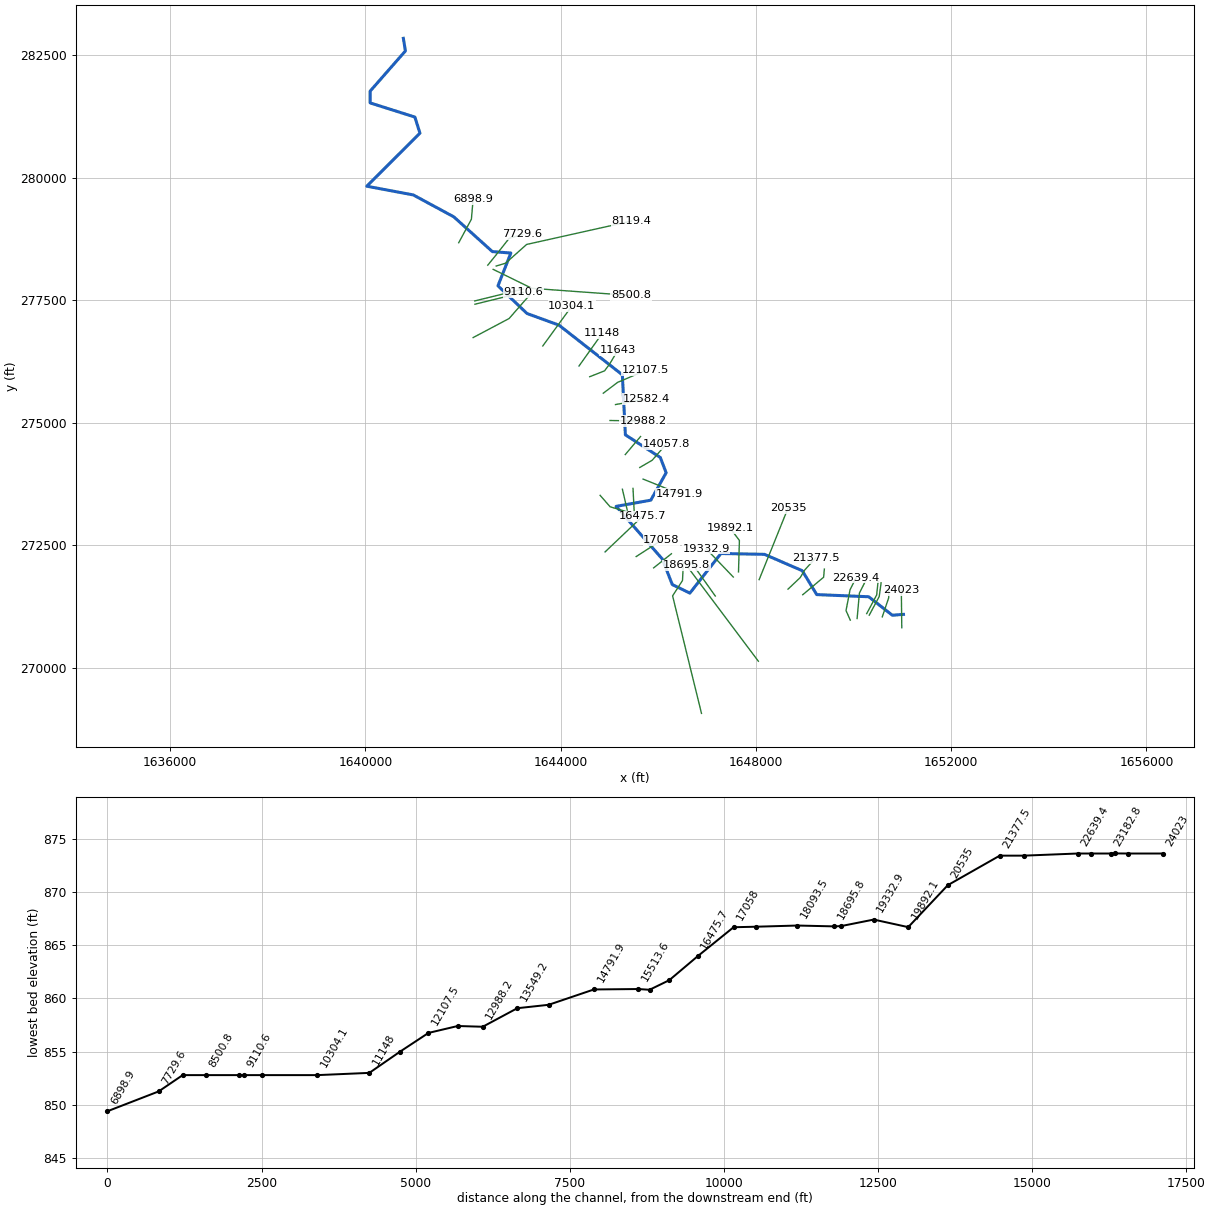
--- BUCKEYCK1.prj (project) ---

Proj Title=BUCKEYCK1
Current Plan=p01
Default Exp/Contr=0,0
English Units
Geom File=g01
Flow File=f01
Plan File=p01
BEGIN DESCRIPTION:
END DESCRIPTION:
DSS Export Rating Curves= 0
DSS Export Rating Curve Sorted= 0
DSS Export Volume Flow Curves= 0
DXF OffsetX= 0
DXF OffsetY= 0
DXF ScaleX= 0
DXF ScaleY= 0

--- BUCKEYCK1.p01 (plan) ---

Plan Title=Floodplain
Program Version=4.00
Geom File=g01
Flow File=f01
K Sum by GR=0
Std Step Tol=0.01
Critical Tol=0.01
Num of Std Step Trials=20
Max Error Tol=0.3
Flow Tol Ratio=0.001
Split Flow NTrial=30
Split Flow Tol=0.02
Split Flow Ratio=0.02
Log Output Level=0
Friction Slope Method=1
Unsteady Friction Slope Method=2
Unsteady Bridges Friction Slope Method=1
Global Log Level=0
CheckData=False
Run HTab=0
Run UNet=0
Run PostProcess=0
UNET Theta=0
UNET Theta Warmup=0
UNET ZTol=0
UNET ZSATol=0
UNET MxIter=0
UNET MaxInSteps=0
UNET DtIC=0
UNET DtMin=0
UNET MaxCRTS=0
UNET WFStab=0
UNET SFStab=0
UNET WFX=0
UNET SFX=0
UNET DSS MLevel=0
UNET DZMax Abort=0
UNET Convert EG Bridges=0
UNET Use Existing IB Tables=0
UNET Froude Limit=0
UNET Froude Power=0
Write IC File=0
Echo Input=False
Echo Output=False
Write Detailed=0

--- BUCKEYCK1.f01 (steady flow) ---

Flow Title=NFF Regression Equation
Program Version=4.10
Number of Profiles= 1
Profile Names=P100yr
River Rch & RM=BUCKEYCK1,Main            ,24023
2002.009
River Rch & RM=BUCKEYCK1,Main            ,23458.9
2559.517
River Rch & RM=BUCKEYCK1,Main            ,18093.5
2698.215
River Rch & RM=BUCKEYCK1,Main            ,17425.2
3017.657
River Rch & RM=BUCKEYCK1,Main            ,8119.4
3279.064
River Rch & RM=BUCKEYCK1,Main            ,7729.6
3779.097
River Rch & RM=BUCKEYCK1,Main            ,437.3
3975.333
River Rch & RM=BUCKEYCK1,Main            ,249.7
 3982.59
Boundary for River Rch & Prof#=BUCKEYCK1,Main            , 1
Up Type= 0
Dn Type= 3
Dn Slope=0.00336
DSS Import GetInterval= 0
DSS Import GetPeak= 0
DSS Import FillOption= 0

--- BUCKEYCK1.g01 (geometry) ---

Geom Title=USGS 10m DEM
Program Version=4.10

River Reach=BUCKEYCK1       ,Main
Reach XY= 30
     1651022.579      271094.971     1650794.329      271076.864
     1650310.933      271454.198     1649246.238       271498.05
      1648948.45      271986.546     1648173.385      272320.027
      1647283.08      272336.344     1646647.149      271528.546
     1646286.945      271702.838     1646082.364      272224.483
     1645136.184      273298.267     1645846.253      273424.136
     1646161.357      273984.031     1646041.566      274295.663
     1645326.288      274757.469     1645263.788      275982.295
     1643966.045      276995.316     1643310.663      277233.163
     1642716.045      277797.399     1642980.264      278466.367
     1642601.097      278496.082      1641810.67      279205.684
      1640979.83      279652.602     1640028.941      279829.705
     1641117.709       280912.53       1641014.3      281240.587
      1640097.88       281529.42      1640097.88       281769.52
     1640820.556      282589.662     1640778.094      282846.856

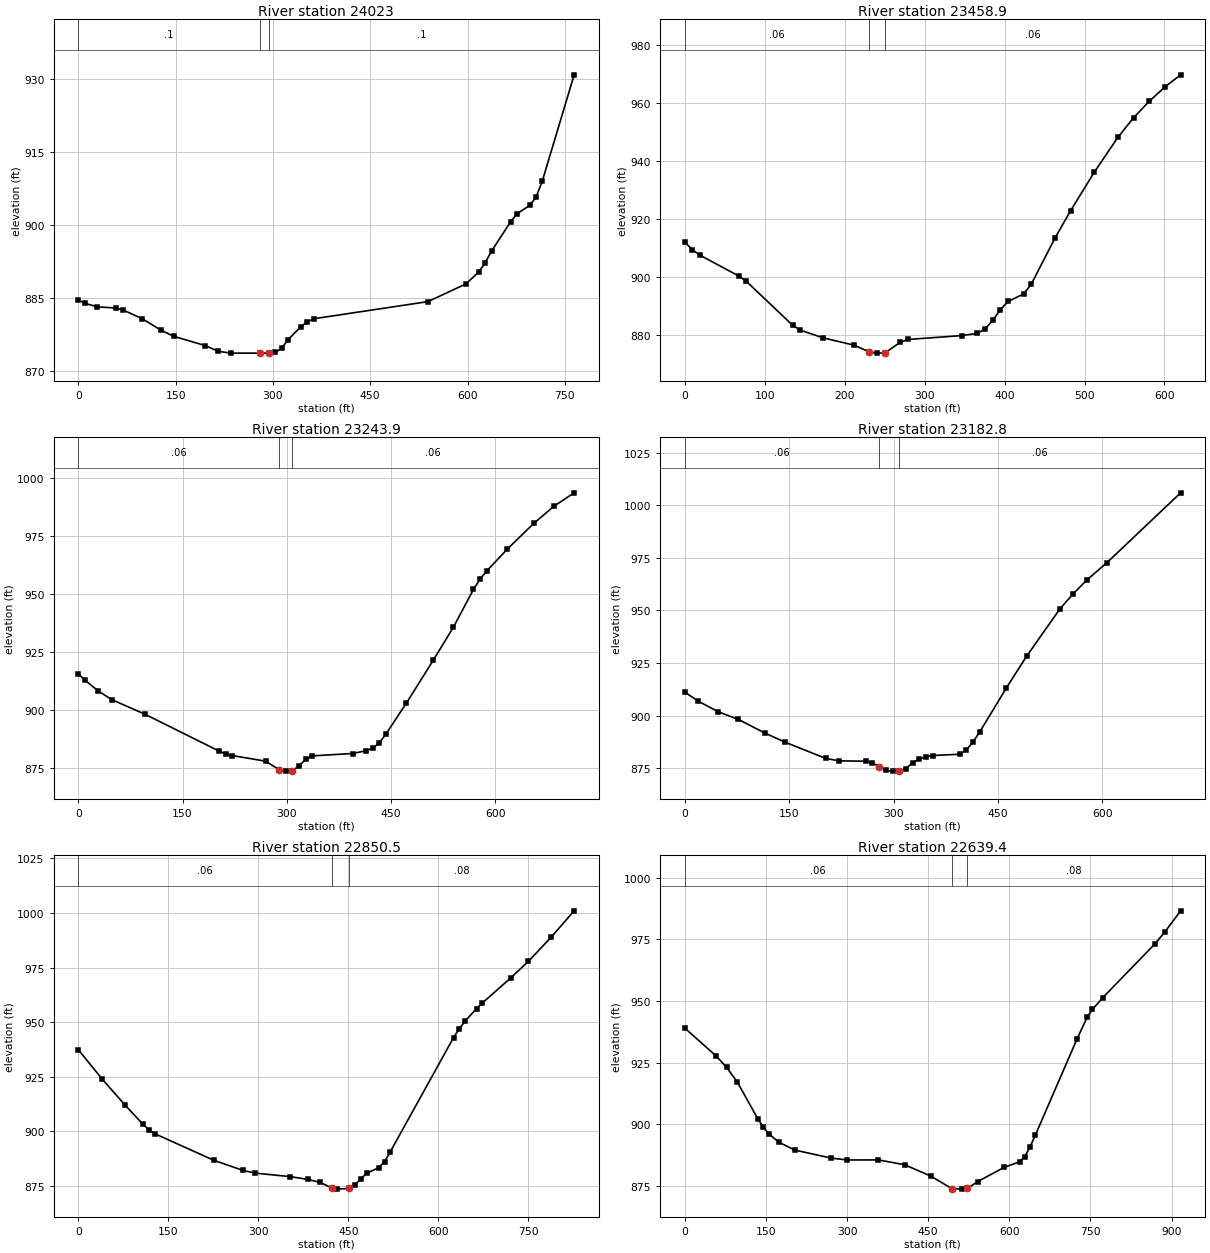
Type RM Length L Ch R = 1 ,24023   ,568.1,564,558.1
XS GIS Cut Line= 2
     1650987.934      270821.652     1650978.819      271585.975
#Sta/Elev= 30
       0  884.55     9.8  883.87    29.4  883.13    58.8  882.88    68.6  882.51
      98  880.72   127.4  878.33     147  877.06     196  875.14   215.6  873.98
   235.2   873.6   279.5   873.6   294.5  873.61   303.8  873.74   313.6  874.64
   323.4  876.38     343  879.05   352.8  880.03   362.6  880.67     539  884.21
   597.8  887.87   617.4  890.34   627.2  892.19     637   894.6   666.4  900.64
   676.2   902.3   695.8  904.01   705.6   905.7   715.4  909.08   764.4  930.91
#Mann= 3 , 0 , 0
       0      .1       0   279.5    .045       0   294.5      .1       0
Bank Sta=279.5,294.5
XS Rating Curve= 0 ,0
Exp/Cntr=0.3,0.1

Type RM Length L Ch R = 1 ,23458.9 ,218.9,215,211.2
XS GIS Cut Line= 3
     1650588.864      271043.822     1650720.809      271436.183
     1650720.809      271642.419
#Sta/Elev= 30
       0  911.93     9.6  909.26    19.2  907.38    67.4  900.25      77  898.38
   134.8  883.25   144.4  881.53   173.3  878.86   211.8  876.34     231  873.98
   240.7   873.6   250.3  873.66   269.6  877.36   279.2  878.32   346.6  879.66
   365.8  880.42   375.4  881.89   385.1  884.87   394.7  888.58   404.3  891.44
   423.8  894.02   433.6  897.52   463.1  913.35   482.7  922.84   512.2  936.08
   541.6  948.07   561.3  954.86   580.9  960.56   600.6  965.53   620.2   969.7
#Mann= 3 , 0 , 0
       0     .06       0     231    .045       0   250.3     .06       0
Bank Sta=231,250.3
XS Rating Curve= 0 ,0
Exp/Cntr=0.3,0.1

Type RM Length L Ch R = 1 ,23243.9 ,60.9,61.1,61.2
XS GIS Cut Line= 3
     1650321.503      271078.544     1650526.364      271460.489
     1650564.559      271738.267
#Sta/Elev= 30
       0   915.6     9.6  912.87    28.9  908.15    48.2  904.48    96.3  898.11
   202.3  882.31   211.9  881.03   221.5  880.33   269.7   877.9   288.9  874.27
   298.6  873.61   308.2  873.82   317.8  875.88   327.5  878.74   337.1   880.2
   394.9  881.22   414.2  882.41   423.8  883.49   433.4  885.83   443.1  889.75
   472.1  902.89   510.8   921.4   539.8  935.66   568.8  952.05   578.4  956.54
   588.1  960.07   617.1  969.33   655.8  980.63   684.8  988.01   713.8  993.77
#Mann= 3 , 0 , 0
       0     .06       0   288.9    .045       0   308.2     .06       0
Bank Sta=288.9,308.2
XS Rating Curve= 0 ,0
Exp/Cntr=0.3,0.1

Type RM Length L Ch R = 1 ,23182.8 ,323.3,332.4,341.3
XS GIS Cut Line= 3
      1650269.42      271109.794     1650474.281      271491.739
     1650502.059      271769.517
#Sta/Elev= 30
       0  911.16    19.3  906.86    48.2  901.81      77  898.18   115.6  891.62
   144.5  887.31   202.3  879.68   221.5  878.48     260  878.32   269.7  877.59
   279.3  875.68   288.9  873.91   298.6   873.6   308.2  873.74   317.8  874.82
   327.5   877.6   337.1   879.4   346.7  880.49   356.4  881.02   394.9  881.63
   404.5  883.63   414.2  887.46   423.8  892.19   462.3  913.24   491.2  928.22
   539.3  950.84   558.6  958.06   577.8  964.47   606.7  972.74   712.6 1005.95
#Mann= 3 , 0 , 0
       0     .06       0   279.3    .045       0   308.2     .06       0
Bank Sta=279.3,308.2
XS Rating Curve= 0 ,0
Exp/Cntr=0.3,0.1

Type RM Length L Ch R = 1 ,22850.5 ,213.4,211,208.7
XS GIS Cut Line= 3
     1650073.054      271010.075     1650119.929      271528.304
      1650257.95      271801.742
#Sta/Elev= 30
       0  937.41    39.3  924.11    78.5  911.87     108   903.2   117.8  900.77
   127.6  898.95   225.8   886.8   274.9  882.13   294.5  880.94   353.4  879.31
   382.9  878.03   402.5  876.73   422.2  874.18     432   873.6   451.6  873.91
   461.4  875.63   471.3  878.45   481.1  880.88   500.7  883.42   510.5  886.22
   520.3  890.81   625.6  942.98   635.2  947.06   644.8  950.48   663.9  956.24
   673.5  958.76   721.4  970.39   750.1  977.77   788.4  988.93   826.6 1000.95
#Mann= 3 , 0 , 0
       0     .06       0   422.2    .045       0   451.6     .08       0
Bank Sta=422.2,451.6
XS Rating Curve= 0 ,0
Exp/Cntr=0.3,0.1

Type RM Length L Ch R = 1 ,22639.4 ,883.1,867.7,852.1
XS GIS Cut Line= 4
     1649932.614       270977.85     1649845.809      271172.294
     1649929.142      271599.378      1650050.67      271838.961
#Sta/Elev= 30
       0  938.98    58.1  927.64    77.4  923.02    96.8  917.17   135.5  901.98
   145.2  898.73   154.9  896.11   174.2  892.59   203.3  889.47     271  886.19
     300  885.44     358  885.46   406.3  883.51   454.7  878.91   493.4  873.85
   512.7   873.6   522.4  873.86   541.7  876.69   590.1   882.4   619.1  884.71
   628.7  886.83   638.4  890.78   648.1  895.52   724.8  934.41     744  943.45
   753.6  946.56   772.8  951.36   868.8   973.1   887.9  978.13   916.7  986.61
#Mann= 3 , 0 , 0
       0     .06       0   493.4    .045       0   522.4     .08       0
Bank Sta=493.4,522.4
XS Rating Curve= 0 ,0
Exp/Cntr=0.3,0.1

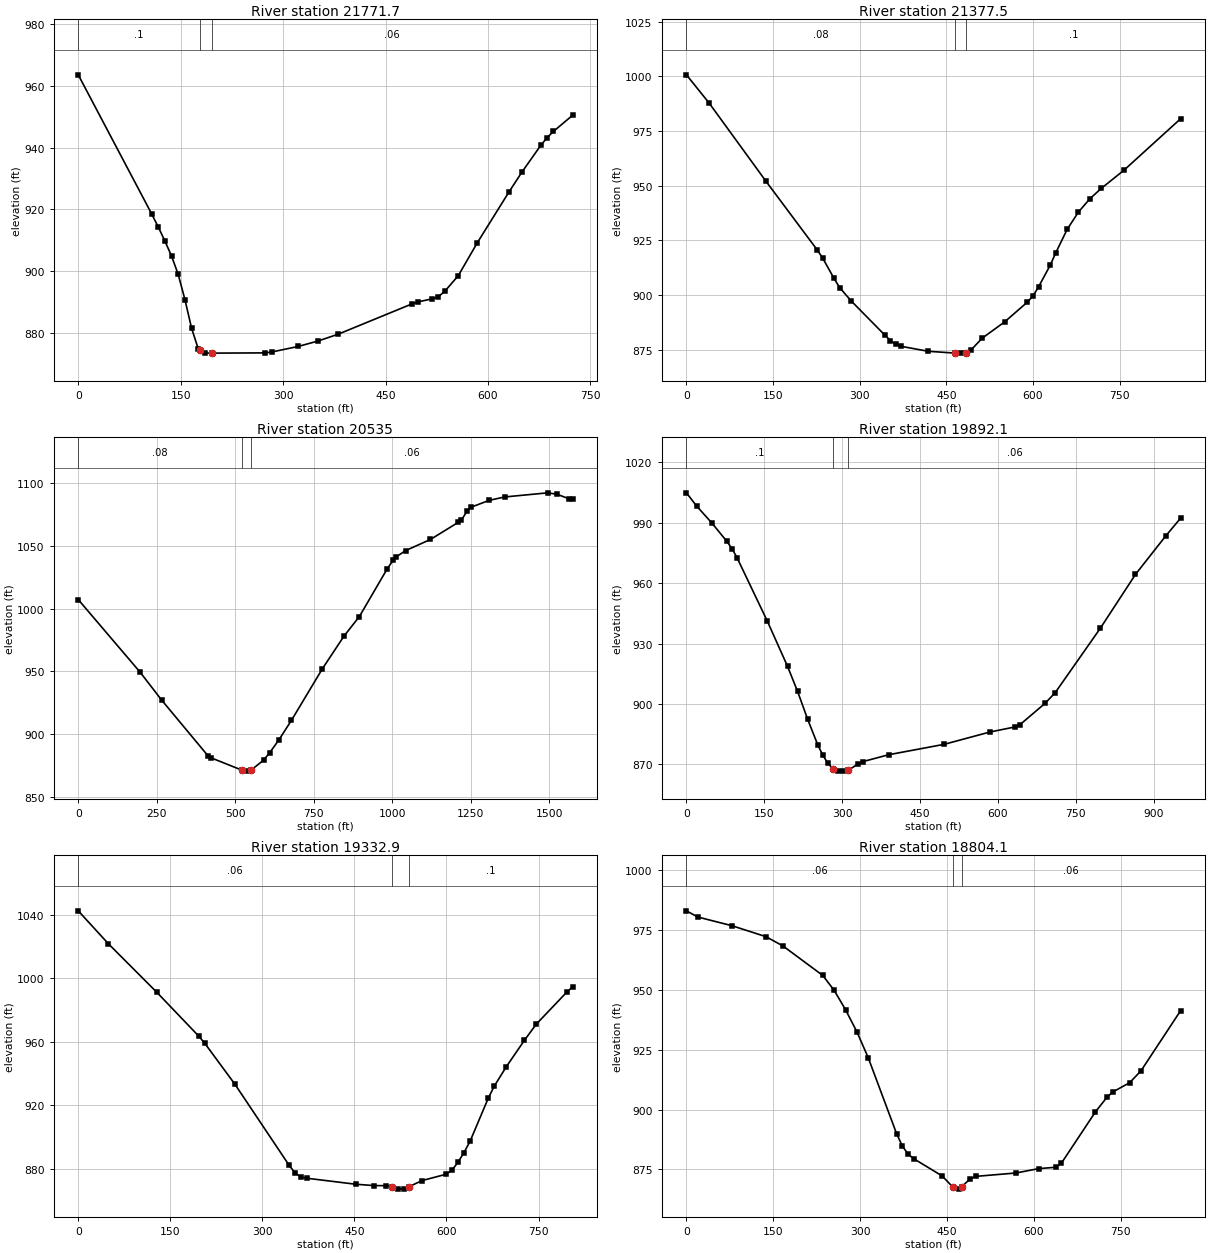
Type RM Length L Ch R = 1 ,21771.7 ,384.1,394.3,403.9
XS GIS Cut Line= 3
     1648959.466      271495.392     1649386.549      271852.163
     1649402.174       272018.83
#Sta/Elev= 30
       0  963.65   107.4   918.6   117.2  914.29   126.9  909.77   136.7  904.84
   146.4  898.92   156.2  890.79     166  881.47   175.7   874.8     178  874.48
   185.5  873.43   195.3   873.4   273.4  873.48   283.1  873.75   322.2  875.57
   351.5  877.35   380.8  879.55   488.2  889.31   497.9  890.02   517.4  890.97
   527.2  891.66     537   893.5   556.5  898.49   584.4  909.18   630.9  925.69
   649.5  932.01   677.4  940.78   686.7  943.28     696  945.32   723.9   950.5
#Mann= 3 , 0 , 0
       0      .1       0     178    .045       0   195.3     .06       0
Bank Sta=178,195.3
XS Rating Curve= 0 ,0
Exp/Cntr=0.3,0.1

Type RM Length L Ch R = 1 ,21377.5 ,840.5,842.5,844
XS GIS Cut Line= 4
     1648658.309      271609.794     1648908.309      271845.905
     1648998.587      271998.683     1649224.281      272245.211
#Sta/Elev= 30
       0 1000.68    39.3  987.76   137.6  952.03     226  920.74   235.8  916.88
   255.4  907.61   265.3  903.36   284.9  897.35   343.9  881.52   353.2  879.14
   362.6  877.38   371.9   876.5   418.6  874.24   465.3  873.41   474.6   873.4
     484  873.63   493.3  875.03     512  880.24   550.8  887.68   590.1  896.71
     600  899.56   609.8  903.83   629.5  913.49   639.3  919.26     659  929.98
   678.6  937.93   698.3  943.97   717.9   948.7   757.3  957.03   855.6  980.63
#Mann= 3 , 0 , 0
       0     .08       0   465.3    .045       0     484      .1       0
Bank Sta=465.3,484
XS Rating Curve= 0 ,0
Exp/Cntr=0.3,0.1

Type RM Length L Ch R = 1 ,20535   ,635.1,642.9,650.6
XS GIS Cut Line= 2
     1648066.237      271803.335     1648657.382      273261.668
#Sta/Elev= 30
       0 1007.14   196.7  949.45   265.5  927.17   413.1  882.81   422.9   881.2
   521.2  871.39   540.9  870.63   550.8  871.57   590.1  879.37   609.8  885.38
   639.3  895.68   678.6  910.99     777     952   845.8  978.01     895  993.66
   983.5 1031.56  1003.2 1038.72    1013  1041.3  1042.5 1046.16  1121.2 1054.99
  1209.7  1068.6  1219.5 1070.33  1239.2 1077.98    1249  1080.5    1308  1086.1
  1357.2 1088.81  1494.9 1092.11  1524.4 1090.96  1563.8 1087.24  1573.6 1086.96
#Mann= 3 , 0 , 0
       0     .08       0   521.2    .045       0   550.8     .06       0
Bank Sta=521.2,550.8
XS Rating Curve= 0 ,0
Exp/Cntr=0.3,0.1

Type RM Length L Ch R = 1 ,19892.1 ,539.6,559.2,578.4
XS GIS Cut Line= 3
     1647643.367      271960.596     1647661.781       272602.85
     1647474.281      272849.378
#Sta/Elev= 30
       0 1004.83    19.5   998.3    48.7  989.93    77.9  980.72    87.6  977.19
    97.4  972.68   155.8  941.16   194.7  918.74   214.2  906.22   233.6  892.37
   253.1  879.67   262.8  874.58   272.6  870.55   282.3   867.8   291.8  866.78
   301.8  866.69   311.5  867.05     331  870.33   340.7  871.46   389.4  874.82
   496.5  879.99   584.1  886.07   632.8  888.62   642.5  889.74   690.9  900.34
   710.3  905.59   797.4  937.62   865.1  964.35   923.2  983.37   952.2  992.31
#Mann= 3 , 0 , 0
       0      .1       0   282.3    .045       0   311.5     .06       0
Bank Sta=282.3,311.5
XS Rating Curve= 0 ,0
Exp/Cntr=0.3,0.1

Type RM Length L Ch R = 1 ,19332.9 ,532.4,528.8,525
XS GIS Cut Line= 2
     1647536.781      271856.322     1646977.753      272436.183
#Sta/Elev= 30
       0 1042.37    49.1 1021.66   127.7  991.27   196.4  963.56   206.3  959.02
   255.4  933.27   343.8  882.29   353.6  877.47   363.4  874.91   373.3  874.21
   451.8  870.49   481.3  869.64     501  869.56   510.8     869   520.6  867.64
   530.4   867.4   538.5  868.83   559.9  872.74   599.2  876.73     609  879.33
   618.8  884.32   628.6  890.42   638.5  897.52   667.9   924.4   677.8   932.1
   697.4  944.29   726.9  960.91   746.5  971.19   795.6  991.06   805.4  994.54
#Mann= 3 , 0 , 0
       0     .06       0   510.8    .045       0   538.5      .1       0
Bank Sta=510.8,538.5
XS Rating Curve= 0 ,0
Exp/Cntr=0.3,0.1

Type RM Length L Ch R = 1 ,18804.1 ,107.7,108.2,108.8
XS GIS Cut Line= 2
     1647168.092      271468.756     1646671.564        272163.2
#Sta/Elev= 30
       0  983.06    19.6  980.47    78.5  976.85   137.4  972.26   166.8  968.37
   235.5  956.06   255.1  949.86   274.8  941.75   294.4  932.53     314  921.69
   363.1  889.88   372.9   884.8   382.7  881.44   392.5  879.51   441.6  872.31
   460.4  867.59     471  866.79   475.4   867.8   490.6  871.19   500.4  872.13
   569.1  873.53   608.4  875.36   637.8  875.92   647.6   877.6   706.5   899.1
   726.1  905.09   735.9  907.31   765.4  911.24     785  916.17   853.7  941.41
#Mann= 3 , 0 , 0
       0     .06       0   460.4    .045       0   475.4     .06       0
Bank Sta=460.4,475.4
XS Rating Curve= 0 ,0
Exp/Cntr=0.3,0.1

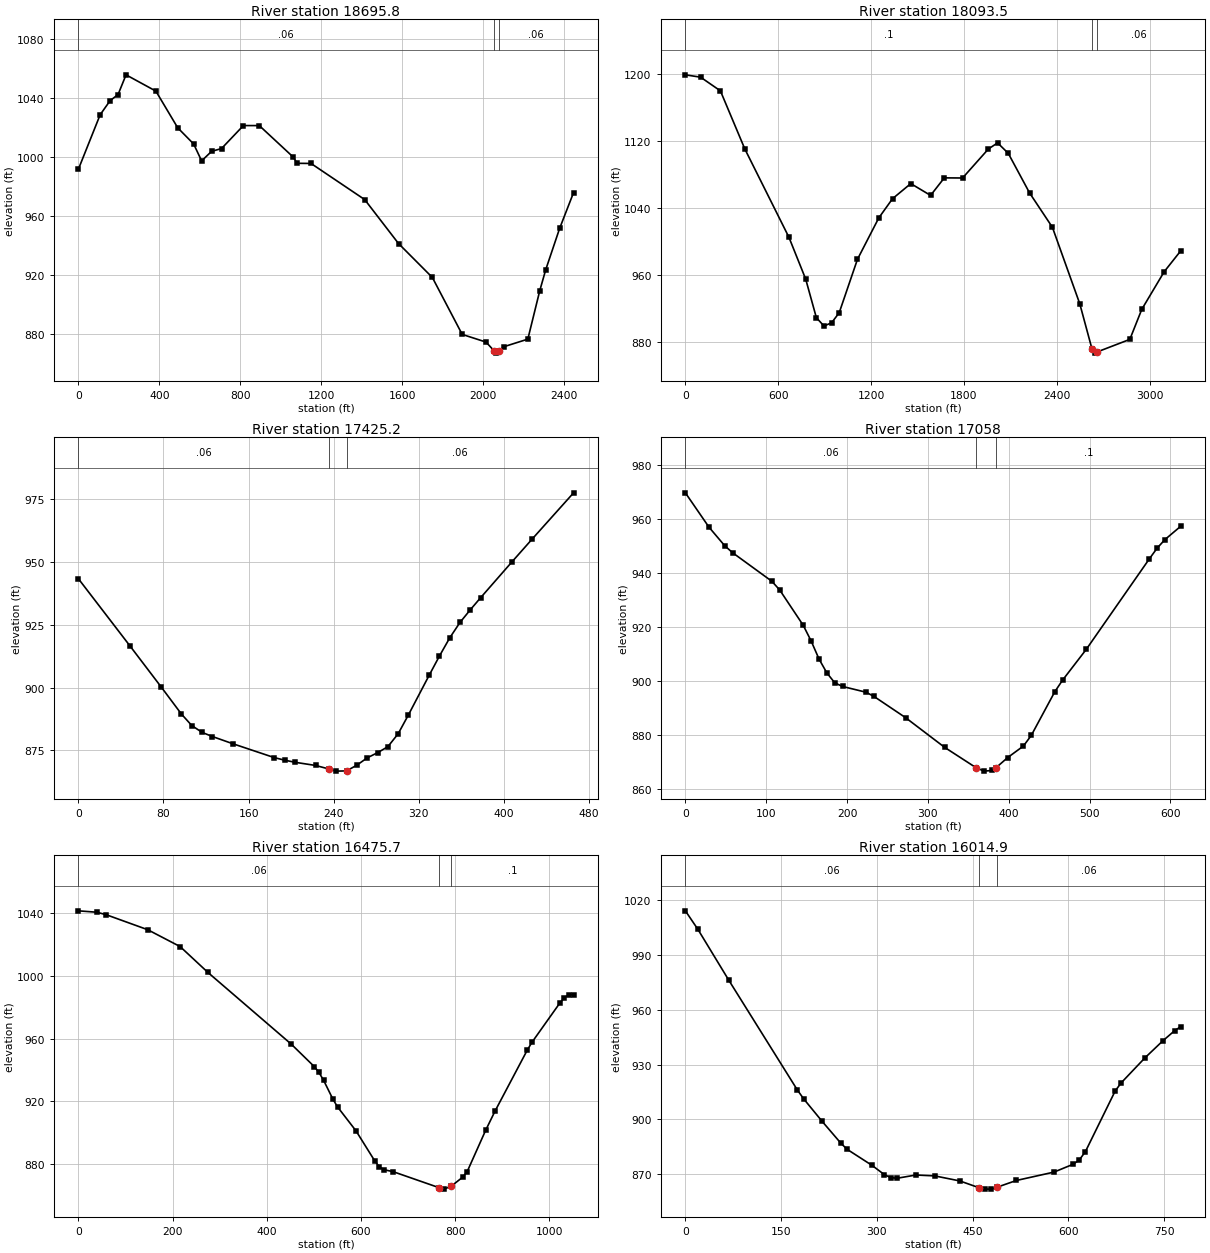
Type RM Length L Ch R = 1 ,18695.8 ,630.3,602.3,574.3
XS GIS Cut Line= 2
     1648050.036      270138.895     1646578.448      272092.433
#Sta/Elev= 30
       0  991.58     108 1028.79   157.2 1038.36   196.4  1042.5   235.7 1055.89
   383.1 1044.82   491.1 1019.86   569.7 1008.88     609   997.4   658.1 1003.88
   707.2 1005.78   815.3 1021.41   893.8 1021.39  1060.8 1000.06  1080.5  995.76
  1149.2  995.66  1414.4  971.09  1581.4  941.23  1748.4  918.17  1895.7  879.49
  2013.6  874.26  2052.9  868.38  2062.7  866.76  2077.1  868.04    2102  871.14
  2219.9  876.27  2278.8  909.19  2308.3  923.46    2377  951.57  2445.8  975.89
#Mann= 3 , 0 , 0
       0     .06       0  2052.9    .045       0  2077.1     .06       0
Bank Sta=2052.9,2077.1
XS Rating Curve= 0 ,0
Exp/Cntr=0.3,0.1

Type RM Length L Ch R = 1 ,18093.5 ,675.6,668.3,661
XS GIS Cut Line= 4
       1646885.2      269074.897     1646293.131      271472.511
     1646495.983      271785.142     1646514.212      272141.912
#Sta/Elev= 30
       0 1199.47    98.4 1196.66   226.3 1180.31   383.7 1111.01   669.1 1005.26
   777.3  955.31   846.2  909.22   895.4  899.25   944.6  903.11   993.8  915.13
  1111.8  979.02  1249.6  1028.5  1338.1 1051.38  1456.2 1069.47  1584.1 1055.36
  1672.7 1076.32  1790.7 1076.16    1958 1110.92    2017 1118.12  2085.9 1105.66
  2223.7 1058.28  2371.2 1017.21  2548.1   925.7  2626.6  871.93  2646.2  866.84
    2656  867.97  2871.3  883.27  2948.5  919.18  3093.3  964.16  3199.6  988.98
#Mann= 3 , 0 , 0
       0      .1       0  2626.6    .045       0    2656     .06       0
Bank Sta=2626.6,2656
XS Rating Curve= 0 ,0
Exp/Cntr=0.3,0.1

Type RM Length L Ch R = 1 ,17425.2 ,369.6,367.2,364.9
XS GIS Cut Line= 2
     1645904.778      272042.918     1646269.362      272331.981
#Sta/Elev= 30
       0  943.36    48.5  916.59    77.6  900.38    96.9  889.44   106.6  884.88
   116.3  882.15     126   880.5   145.4   877.6   184.2   872.1   193.9  871.09
   203.6  870.25   222.9  868.99   235.2  867.61   242.3  866.73     252  866.82
   261.7   869.1   271.4  872.01   281.1  874.06   290.8  876.45   300.5  881.61
   310.2  889.16   329.6  904.87   339.3  912.56     349  919.81   358.6  925.93
   368.3  930.97     378  935.78   407.1  949.88   426.5  959.16   465.3  977.51
#Mann= 3 , 0 , 0
       0     .06       0   235.2    .045       0     252     .06       0
Bank Sta=235.2,252
XS Rating Curve= 0 ,0
Exp/Cntr=0.3,0.1

Type RM Length L Ch R = 1 ,17058   ,578,582.3,586.3
XS GIS Cut Line= 2
     1645548.066      272274.725     1646063.691      272605.454
#Sta/Elev= 30
       0  969.67    29.2  956.96    48.6  950.11    58.3  947.53     107  936.93
   116.7  933.71   145.8  920.63   155.6  914.81   165.3  908.17     175  903.02
   184.8  899.35   194.5     898   223.6  895.87   233.4   894.3   272.3  886.48
   320.9  875.43   359.8   867.9   369.5  866.68   379.2  866.92   384.1  867.91
   398.7  871.71   418.1  875.96   427.8  879.87     457   896.1   466.7  900.41
   495.9  911.76   573.7  945.16   583.4  949.16   593.1  952.35   612.6  957.28
#Mann= 3 , 0 , 0
       0     .06       0   359.8    .045       0   384.1      .1       0
Bank Sta=359.8,384.1
XS Rating Curve= 0 ,0
Exp/Cntr=0.3,0.1

Type RM Length L Ch R = 1 ,16475.7 ,489.3,460.8,428.2
XS GIS Cut Line= 2
     1644910.045      272368.996     1645673.734      273091.846
#Sta/Elev= 30
       0 1041.63    39.3 1040.73      59 1039.17   147.4 1029.57   216.2  1018.8
   275.2 1002.29   452.1  956.52   501.2  942.12     511  938.42   520.9  933.36
   540.5  921.41   550.3  916.48   589.6  901.15     629  882.17   638.8   878.3
   648.6  876.38   668.3  875.11   766.5  864.83   776.4  863.96   791.6   865.8
   815.7  871.51   825.5  875.06   864.8   901.5   884.5  913.63   953.3  952.78
   963.1  957.68  1022.1  982.67  1031.9  986.14  1041.7  988.15  1051.5  988.19
#Mann= 3 , 0 , 0
       0     .06       0   766.5    .045       0   791.6      .1       0
Bank Sta=766.5,791.6
XS Rating Curve= 0 ,0
Exp/Cntr=0.3,0.1

Type RM Length L Ch R = 1 ,16014.9 ,339.7,319.8,304.1
XS GIS Cut Line= 4
     1644808.483      273523.683     1645014.212      273289.308
     1645316.295      273200.767     1645451.712      273138.267
#Sta/Elev= 30
       0 1014.32    19.5 1004.22    68.2  976.16   175.4  916.08   185.2  911.26
   214.4   898.8   243.6  886.88   253.4  883.53   292.4  874.73   311.9   869.6
   321.7  868.06   331.5  867.66     361  869.45   390.6  868.97   429.9   866.2
   459.4  862.55   469.3  861.72   479.1  861.71   488.9  862.84   518.4  866.45
   577.5  871.06     607   875.3   616.8   877.6   626.6  882.27   673.3  915.56
   682.6  919.97   719.9  933.71   747.8     943   766.5  948.64   775.8  950.78
#Mann= 3 , 0 , 0
       0     .06       0   459.4    .045       0   488.9     .06       0
Bank Sta=459.4,488.9
XS Rating Curve= 0 ,0
Exp/Cntr=0.3,0.1

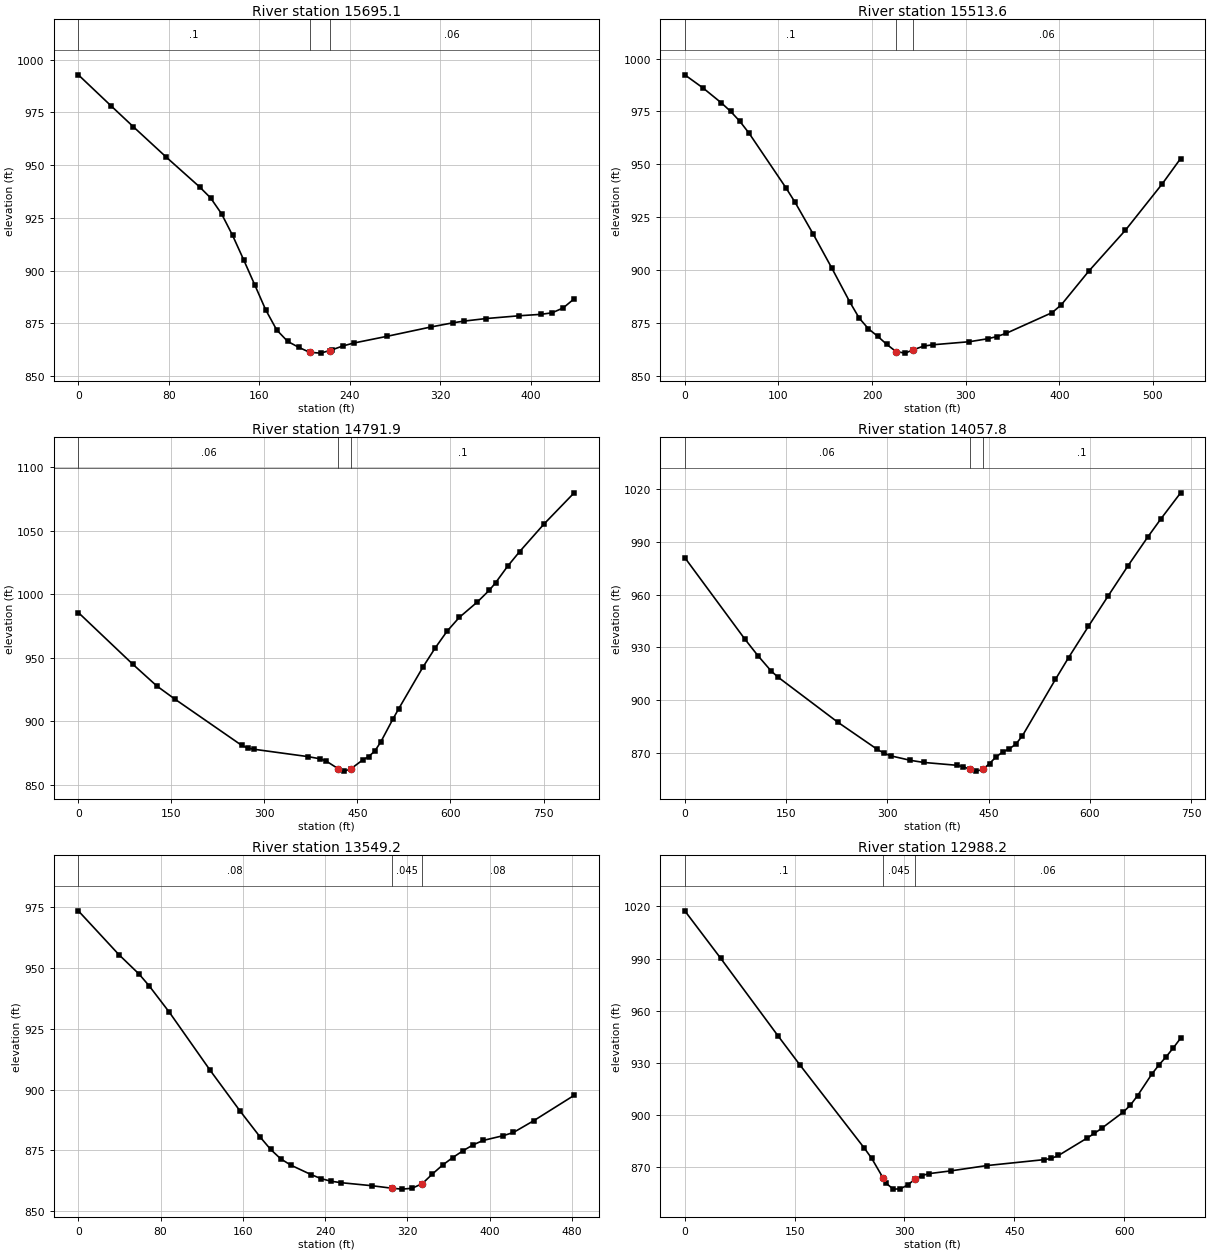
Type RM Length L Ch R = 1 ,15695.1 ,185.5,181.4,177.4
XS GIS Cut Line= 2
     1645265.198      273648.081     1645364.157      273220.998
#Sta/Elev= 30
       0  992.83    29.2  977.98    48.7  968.16    77.9  953.71   107.2  939.67
   116.9  934.47   126.6  926.94   136.4  916.65   146.1  905.17   155.9   893.3
   165.6  881.42   175.4   871.8   185.1  866.37   194.8  863.59   204.6  861.18
   214.3  860.81   222.2  862.04   224.1  862.33   233.8   864.2   243.6   865.6
   272.8  868.77   311.8  873.22   331.2  875.19     341     876   360.5  877.21
   389.7  878.53   409.2  879.22   418.9  879.94   428.7  882.25   438.4  886.58
#Mann= 3 , 0 , 0
       0      .1       0   204.6    .045       0   222.2     .06       0
Bank Sta=204.6,222.2
XS Rating Curve= 0 ,0
Exp/Cntr=0.3,0.1

Type RM Length L Ch R = 1 ,15513.6 ,695.5,721.8,747.8
XS GIS Cut Line= 2
     1645482.776      273664.589     1645509.003      273135.662
#Sta/Elev= 30
       0   992.3    19.6  986.05    39.2     979      49  975.01    58.8  970.35
    68.6  964.76   107.9  939.03   117.7  932.16   137.3  916.98   156.9  901.14
   176.5  884.82   186.3  877.42   196.1  872.38     206  868.85   215.8  864.98
   225.6  861.62   235.4  860.88   243.8  862.43     255  864.19   264.8  864.82
     304  866.27   323.6  867.67   333.4  868.71   343.2  870.22   392.3     880
   402.1  883.67   431.5   899.6   470.7  918.96     510  940.83   529.6  952.78
#Mann= 3 , 0 , 0
       0      .1       0   225.6    .045       0   243.8     .06       0
Bank Sta=225.6,243.8
XS Rating Curve= 0 ,0
Exp/Cntr=0.3,0.1

Type RM Length L Ch R = 1 ,14791.9 ,706.2,734.1,762.1
XS GIS Cut Line= 2
     1645688.691      273854.412     1646430.878      273557.537
#Sta/Elev= 30
       0  985.63    87.7  944.99   126.7  927.77     156  917.39   263.2  881.17
     273  879.02   282.7  878.08   370.4  872.25   389.9  870.52   399.7  868.73
   419.2  862.66   428.9  860.84     439  862.49   458.2  869.52   467.9  872.24
   477.7  876.46   487.4  883.61   506.9  901.56   516.7  910.07   555.6  942.71
   575.2  957.65   594.6     971   614.1  981.74   643.4  993.96   662.9 1003.32
   672.6 1008.99   692.1 1022.05   711.6 1033.63   750.6 1055.18   799.4 1079.82
#Mann= 3 , 0 , 0
       0     .06       0   419.2    .045       0     439      .1       0
Bank Sta=419.2,439
XS Rating Curve= 0 ,0
Exp/Cntr=0.3,0.1

Type RM Length L Ch R = 1 ,14057.8 ,508.4,508.6,508.7
XS GIS Cut Line= 3
     1645620.983      274091.392     1645876.191      274239.829
     1646165.253      274570.558
#Sta/Elev= 30
       0  981.14    88.6  934.87   108.2  925.29   127.9   916.5   137.8  913.09
   226.4  887.37   285.4  871.74   295.2  869.62     305  868.13   334.3  865.55
   353.8  864.36   402.6  862.74   412.4  861.93   422.1   860.5   431.9   859.4
   441.6  860.37   451.4  863.74   461.2  867.54   470.9  870.29   480.7  872.08
   490.5  874.85   500.2   879.6     549  911.69   568.6  924.18   597.8   941.9
   627.1  959.27   656.4  976.42   685.7  992.83   705.2 1003.22   734.5  1018.1
#Mann= 3 , 0 , 0
       0     .06       0   422.1    .045       0   441.6      .1       0
Bank Sta=422.1,441.6
XS Rating Curve= 0 ,0
Exp/Cntr=0.3,0.1

Type RM Length L Ch R = 1 ,13549.2 ,581,561,541
XS GIS Cut Line= 2
     1645324.049      274355.418     1645636.549      274722.606
#Sta/Elev= 30
       0  973.62    39.4  955.61      59  947.62    68.9  942.74    88.6  931.83
   127.9  908.16   157.4  891.16   177.1  880.37     187  875.43   196.8  871.55
   206.6  868.97   226.3  865.07   236.2  863.38     246  862.31   255.8  861.72
   285.4  860.49     305  859.45   314.9  859.08   324.7  859.44   334.6  861.38
   344.4  865.33   354.2  868.96   364.1  872.06   373.9  874.82   383.8  877.27
   393.6  879.11   413.3  881.09   423.1  882.39   442.8  887.22   482.2  897.68
#Mann= 3 , 0 , 0
       0     .08       0     305    .045       0   334.6     .08       0
Bank Sta=305,334.6
XS Rating Curve= 0 ,0
Exp/Cntr=0.3,0.1

Type RM Length L Ch R = 1 ,12988.2 ,401.3,405.8,410.3
XS GIS Cut Line= 2
     1645011.549       275050.08     1645688.691      275039.308
#Sta/Elev= 30
       0 1017.43    49.1  990.08   127.6  945.35     157   928.9   245.4  880.81
   255.2  875.09     271  863.62   274.8  860.82   284.6  857.34   294.4  857.49
   304.3   859.7   314.1  862.94   323.9  865.16   333.7  866.26   363.2  867.83
   412.2  870.88   490.7   874.3   500.6  875.01   510.4  876.71   549.6  886.74
   559.4  889.42   569.3  892.31   598.7   901.6   608.5  905.61   618.3  911.06
     638  923.59   647.8  928.87   657.6  933.56   667.4  938.69   677.2  944.17
#Mann= 3 , 0 , 0
       0      .1       0     271    .045       0   314.1     .06       0
Bank Sta=271,314.1
XS Rating Curve= 0 ,0
Exp/Cntr=0.3,0.1

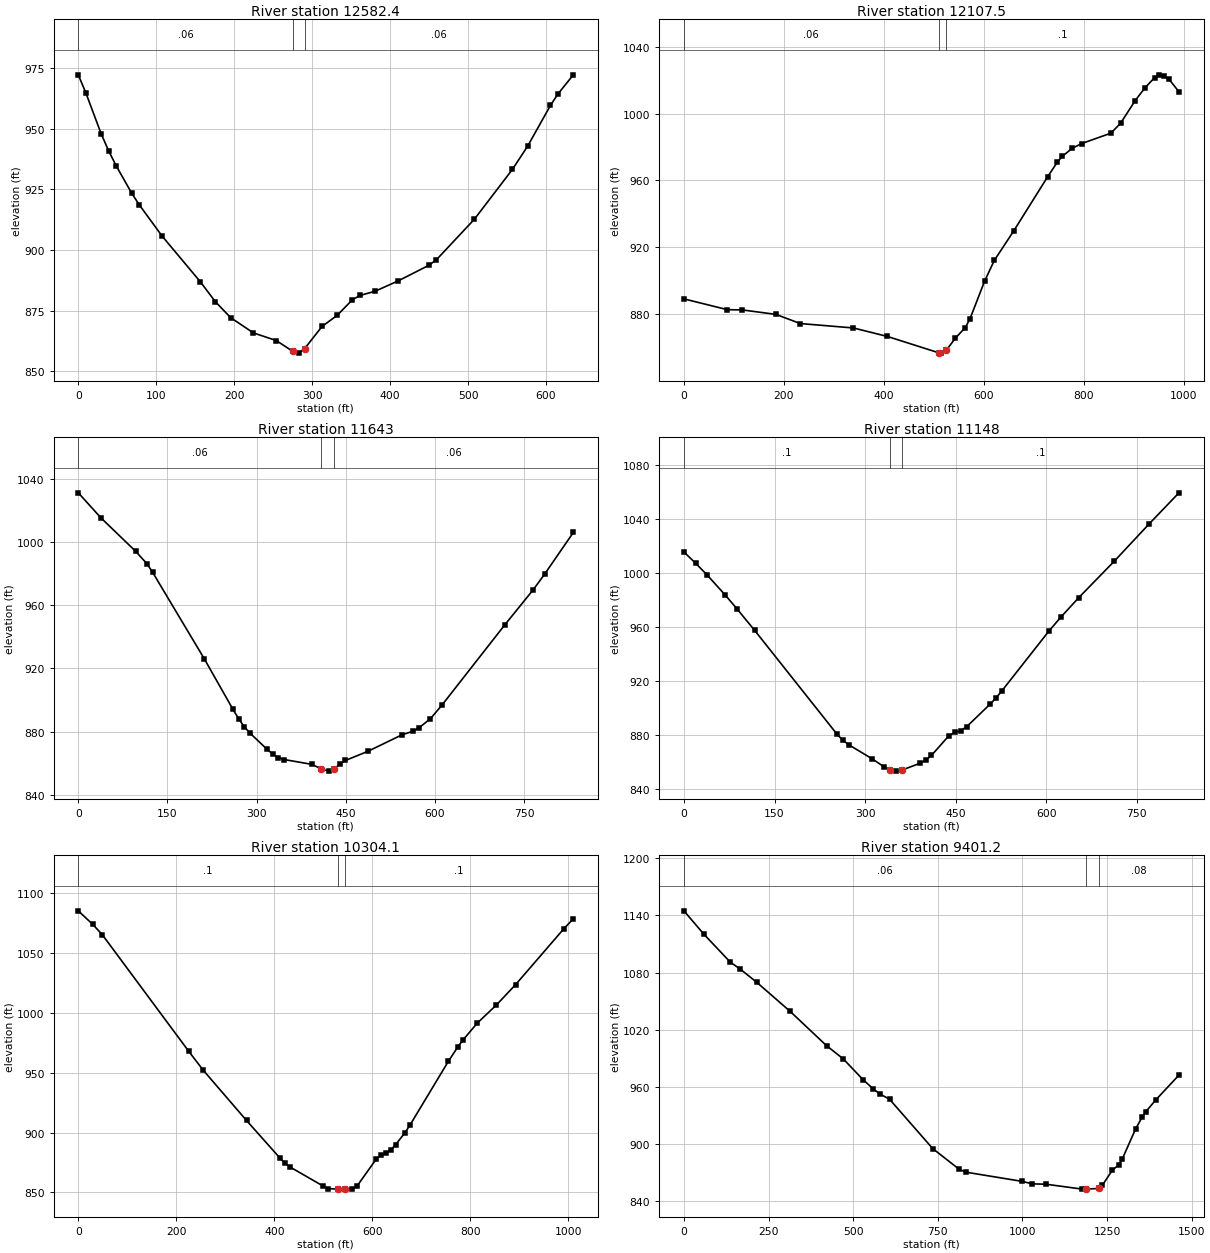
Type RM Length L Ch R = 1 ,12582.4 ,469.9,474.9,480
XS GIS Cut Line= 2
     1645123.587      275375.246     1645748.587      275487.225
#Sta/Elev= 30
       0  972.34     9.8   964.8    29.3  948.01    39.1  940.81    48.8  934.66
    68.4  923.51    78.2  918.66   107.4  905.79   156.3  886.97   175.8  878.66
   195.4  872.07   224.7  865.75     254   862.6   275.3   858.1   283.3  857.41
   290.3  859.26   312.6  868.41   332.1  873.02   351.7   879.5   361.4  881.22
     381     883   410.3  887.24   449.4  893.63   459.1  895.88     508  912.68
   556.8  933.26   576.3  942.83   605.6  959.69   615.4   964.5     635  972.34
#Mann= 3 , 0 , 0
       0     .06       0   275.3    .045       0   290.3     .06       0
Bank Sta=275.3,290.3
XS Rating Curve= 0 ,0
Exp/Cntr=0.3,0.1

Type RM Length L Ch R = 1 ,12107.5 ,452.8,464.5,476.2
XS GIS Cut Line= 3
     1644873.587      275607.017     1645167.858      275828.371
     1645740.589      276070.839
#Sta/Elev= 30
       0  889.19    87.2  882.72   116.3  882.61   184.1  879.92   232.6  874.45
   339.2   871.8   407.1  866.72   509.7  856.97     514  856.76   524.7  858.38
   543.2  865.79   562.6  871.92   572.3  877.32   601.5  899.81   620.9   912.2
   659.8  929.86   727.8  962.31   747.2  971.07   756.9   974.4   776.4  979.16
   795.8  982.07   854.1  988.26   873.6  994.25   902.7 1007.75   922.2 1015.36
   941.6  1021.5   951.3 1023.14     961 1022.36   970.7 1020.37   990.2    1013
#Mann= 3 , 0 , 0
       0     .06       0   509.7    .045       0   524.7      .1       0
Bank Sta=509.7,524.7
XS Rating Curve= 0 ,0
Exp/Cntr=0.3,0.1

Type RM Length L Ch R = 1 ,11643   ,494.2,495.1,495.9
XS GIS Cut Line= 4
     1644594.941      275942.954     1644899.628      276062.746
     1645006.399      276205.975     1645173.066      276487.225
#Sta/Elev= 30
       0 1031.27    38.5 1015.27    96.3   994.3   115.6  986.34   125.2  980.84
   211.8  926.28     260  894.27   269.6   888.3   279.2  883.12   288.9  879.06
   317.8  868.76   327.4  865.69   336.8  863.57   346.2  862.35   393.2  859.26
   409.1  856.35   421.4  854.99   430.8  856.45   440.2  859.47   449.6  861.76
   487.2  867.52   544.5  877.96   563.7  880.32   573.3  882.42   592.6  888.22
   611.8  896.75   717.6  947.61   765.6  969.93   784.9  979.88     833 1006.17
#Mann= 3 , 0 , 0
       0     .06       0   409.1    .045       0   430.8     .06       0
Bank Sta=409.1,430.8
XS Rating Curve= 0 ,0
Exp/Cntr=0.3,0.1

Type RM Length L Ch R = 1 ,11148   ,844.1,843.9,843.6
XS GIS Cut Line= 2
     1644376.191      276161.704     1644852.753      276828.371
#Sta/Elev= 30
       0 1015.62    19.5 1007.25      39  998.28    68.3  983.71    87.8  973.47
   117.1  957.46   253.6  880.32   263.4  875.83   273.2  872.52   312.2  861.97
   331.7   856.1   341.4  853.59   351.2  853.01     361   853.8   390.2  858.73
     400  861.06   409.7  864.63     439  879.41   448.8   881.8   458.5   883.1
   468.3  886.03   507.3   902.9   517.1  907.51   526.8  912.81   604.9  957.29
   624.4  967.46   653.6  981.71   712.2 1008.66   770.7 1036.71   819.5 1059.51
#Mann= 3 , 0 , 0
       0      .1       0   341.4    .045       0     361      .1       0
Bank Sta=341.4,361
XS Rating Curve= 0 ,0
Exp/Cntr=0.3,0.1

Type RM Length L Ch R = 1 ,10304.1 ,905.8,902.8,899.5
XS GIS Cut Line= 2
     1643634.003      276570.558     1644230.358      277385.662
#Sta/Elev= 30
       0 1085.43    29.4 1074.14      49 1065.47   225.5   967.9   254.9   952.2
   343.2  910.18   411.8  878.61   421.6  874.51   431.4  871.43   500.1  855.23
   509.9  853.27   529.4   852.8   544.4   852.8   558.9  853.03   568.7  855.37
   607.9  877.89   617.8  881.28   627.6  882.65   637.4  885.49   647.2  889.82
   666.8  900.12   676.6  906.26     755   959.6   774.6  971.85   784.4  977.23
   813.9  991.53   853.1 1006.74   892.3  1023.8   990.4 1070.34    1010 1078.78
#Mann= 3 , 0 , 0
       0      .1       0   529.4    .045       0   544.4      .1       0
Bank Sta=529.4,544.4
XS Rating Curve= 0 ,0
Exp/Cntr=0.3,0.1

Type RM Length L Ch R = 1 ,9401.2  ,306.7,290.6,272.1
XS GIS Cut Line= 3
     1642206.992      276741.638     1642943.714      277130.214
      1643359.77      277602.749
#Sta/Elev= 30
       0 1144.87    58.8 1120.42   137.2 1090.96   166.6 1083.66   215.6 1069.75
   313.6 1039.43   421.4 1003.35   470.4  989.62   529.2   967.7   558.5   958.3
   578.1  952.86   607.5  947.16   734.9  895.42   813.3   873.6   832.9  870.62
  1000.2  860.88  1029.7   858.3    1069  857.99  1177.2   852.8  1187.1   852.8
  1226.4  853.51  1236.2  856.84  1265.8  872.68  1285.4  878.41  1295.3   884.6
  1334.6  916.09  1354.3  928.76  1364.1  933.81  1393.6  946.26  1462.5  972.44
#Mann= 3 , 0 , 0
       0     .06       0  1187.1    .045       0  1226.4     .08       0
Bank Sta=1187.1,1226.4
XS Rating Curve= 0 ,0
Exp/Cntr=0.3,0.1

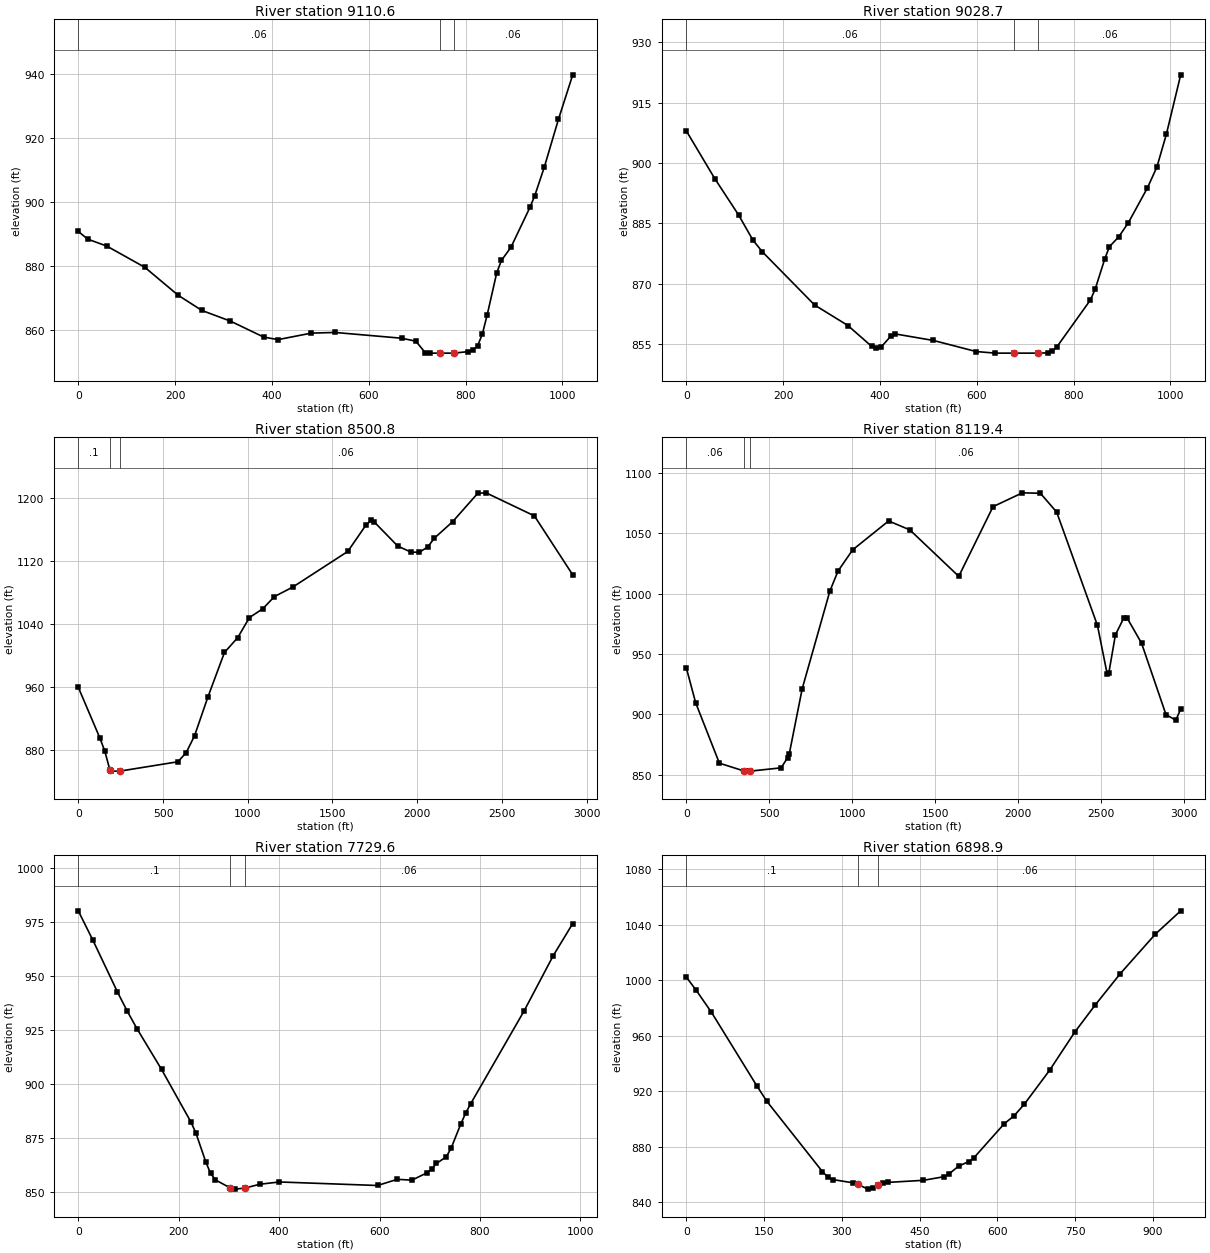
Type RM Length L Ch R = 1 ,9110.6  ,81.7,82,84.6
XS GIS Cut Line= 2
     1642243.378      277422.121     1643235.566      277664.308
#Sta/Elev= 30
       0  890.83    19.6  888.42    58.9  886.26   137.5  879.62   206.2   870.9
   255.3  866.14   314.2  862.81     383  857.82   412.5  857.02   481.2  859.05
   530.3  859.26   667.8  857.46   697.2  856.54   716.9  852.91   726.7   852.8
   746.4   852.8   775.8   852.8   805.3  853.27   815.1  853.77   824.9  855.07
   834.7  858.82   844.6  864.74   864.2  877.81     874  881.77   893.6  885.86
   932.9  898.34   942.8  901.97   962.4  910.83   991.9  925.92  1021.3  939.78
#Mann= 3 , 0 , 0
       0     .06       0   746.4    .045       0   775.8     .06       0
Bank Sta=746.4,775.8
XS Rating Curve= 0 ,0
Exp/Cntr=0.3,0.1

Type RM Length L Ch R = 1 ,9028.7  ,541.9,527.9,513.9
XS GIS Cut Line= 2
     1642240.774      277489.829     1643232.962      277732.017
#Sta/Elev= 30
       0  908.04    58.9  896.16     108  887.15   137.5  880.92   157.1  877.98
   265.2  864.75   333.9  859.66     383  854.48   392.8  854.01   402.6  854.33
   422.3  856.97   432.1  857.56   510.7  855.94     599  853.19   638.3   852.8
   677.6   852.8   726.7   852.8   746.4  852.86   756.2  853.28     766  854.43
   834.7  865.98   844.6  868.66   864.2   876.1     874  879.22   893.6  881.73
   913.3  885.21   952.6  893.85   972.2  899.05   991.9  907.26  1021.3  921.93
#Mann= 3 , 0 , 0
       0     .06       0   677.6    .045       0   726.7     .06       0
Bank Sta=677.6,726.7
XS Rating Curve= 0 ,0
Exp/Cntr=0.3,0.1

Type RM Length L Ch R = 1 ,8500.8  ,350.6,381.3,417.2
XS GIS Cut Line= 3
      1642618.32      278133.413     1643411.344      277746.576
     1645441.442      277600.527
#Sta/Elev= 30
       0  959.34   127.4  894.95   156.9  877.96   186.3  854.47   196.1   852.8
   245.1   852.8   588.2   864.7   637.2  876.42   686.3  897.83   764.7  946.79
   862.7 1003.54   941.3 1022.51  1010.2  1047.9  1088.8 1059.02  1157.7 1074.55
  1265.8 1086.58  1590.3 1131.83  1698.4 1165.57    1728  1171.2  1747.6 1169.04
  1885.3 1138.64  1963.9 1130.95  2013.1 1130.82  2062.2 1137.62  2101.6 1148.75
  2209.7 1169.76  2357.2  1205.7  2406.4  1206.3  2691.5 1176.99  2917.7  1102.1
#Mann= 3 , 0 , 0
       0      .1       0   186.3    .045       0   245.1     .06       0
Bank Sta=186.3,245.1
XS Rating Curve= 0 ,0
Exp/Cntr=0.3,0.1

Type RM Length L Ch R = 1 ,8119.4  ,389.1,389.8,384.7
XS GIS Cut Line= 4
     1642680.343       278201.87     1642871.678      278258.815
     1643303.182      278641.726     1645451.854      279118.892
#Sta/Elev= 30
       0  938.76      57  909.43   199.6  859.41   346.3  852.99     363   852.8
   385.4   852.8   571.2  855.53   610.3  863.84   620.1  866.85   698.3   921.1
     865 1002.16   914.1 1018.79  1002.5 1036.41  1218.7 1060.34  1346.4 1052.95
  1641.2  1014.4  1847.6 1072.21  2024.4 1083.68  2132.5 1083.34  2230.8 1067.68
  2476.4  973.64  2535.4  933.04  2545.2  934.55  2584.5  965.87  2633.6  979.48
  2653.3  980.23  2741.7  959.02  2889.1  899.67  2948.1  895.07  2977.6  904.26
#Mann= 3 , 0 , 0
       0     .06       0   346.3    .045       0   385.4     .06       0
Bank Sta=346.3,385.4
XS Rating Curve= 0 ,0
Exp/Cntr=0.3,0.1

Type RM Length L Ch R = 1 ,7729.6  ,826.6,830.8,835.2
XS GIS Cut Line= 4
     1642507.114      278218.451      1642673.51      278422.816
     1642946.318      278768.235     1643216.611      278845.455
#Sta/Elev= 30
       0     980    29.3  966.33    78.1  942.44    97.6  933.57   117.1  925.42
   165.9  906.63   224.5  882.27   234.3  877.21   253.8  863.99   263.5  858.55
   273.3  855.53   302.7  851.83   312.4  851.27     332  851.76   361.4  853.52
   400.5  854.58   596.1  852.95   635.2   855.8   664.6  855.43   693.9  858.75
   703.7  860.54   713.4  863.13   732.8   866.2   742.5  870.14   761.9  881.44
   771.6  886.46   781.2  890.63   887.9  933.68     946  959.27   984.8  974.11
#Mann= 3 , 0 , 0
       0      .1       0   302.7    .045       0     332     .06       0
Bank Sta=302.7,332
XS Rating Curve= 0 ,0
Exp/Cntr=0.3,0.1

Type RM Length L Ch R = 1 ,6898.9  ,693.6,692.6,691.7
XS GIS Cut Line= 3
     1641912.193      278677.126     1642171.989      279156.306
     1642206.628       279563.32
#Sta/Elev= 30
       0 1002.36    19.5  992.62    48.7  976.87   136.3  923.78   155.7  912.61
   262.8  861.97   272.5  858.38   282.3  856.31   321.2  853.99   330.9  852.82
   350.4  849.41   360.1  850.32   369.9  852.33   379.6  853.77   389.3  854.28
   457.5  855.76   496.4  858.33   506.1  860.17   525.6  866.07   545.1  869.29
   554.8     872   613.2  896.52   632.6  902.38   652.1  910.68   700.7  935.05
   749.3   962.6   788.2  981.89   836.8 1004.64   904.9 1033.29   953.6 1050.04
#Mann= 3 , 0 , 0
       0      .1       0   330.9    .045       0   369.9     .06       0
Bank Sta=330.9,369.9
XS Rating Curve= 0 ,0
Exp/Cntr=0.3,0.1