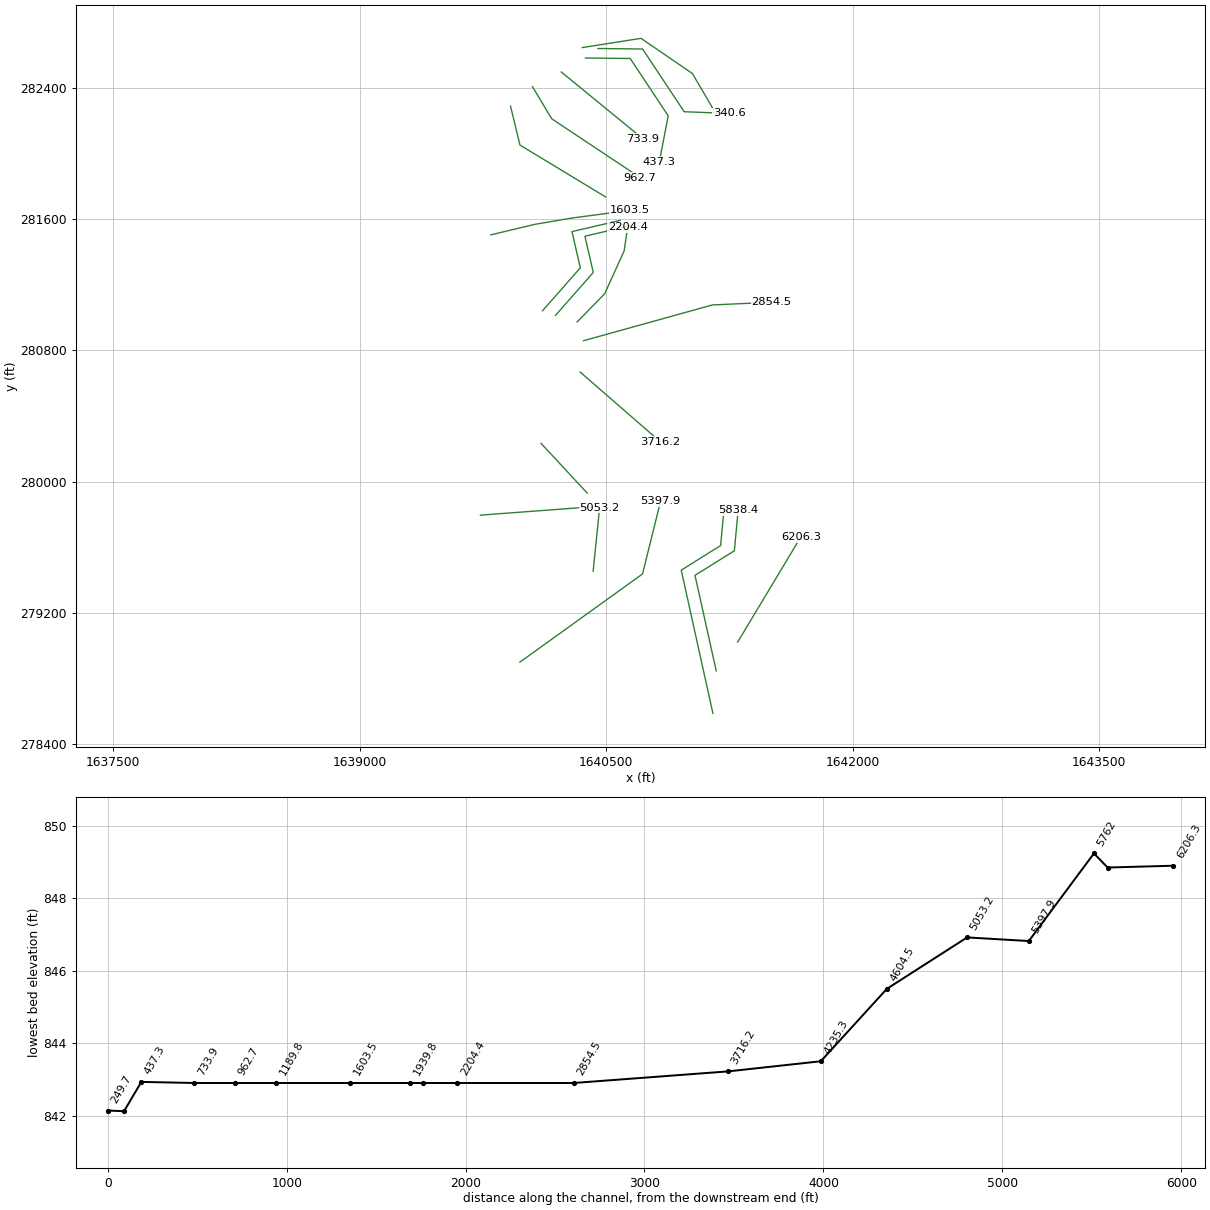
HEC-RAS study BUCKEYCK1.prj: BUCKEYCK1

--- BUCKEYCK1.g01 (geometry) --- (continued)

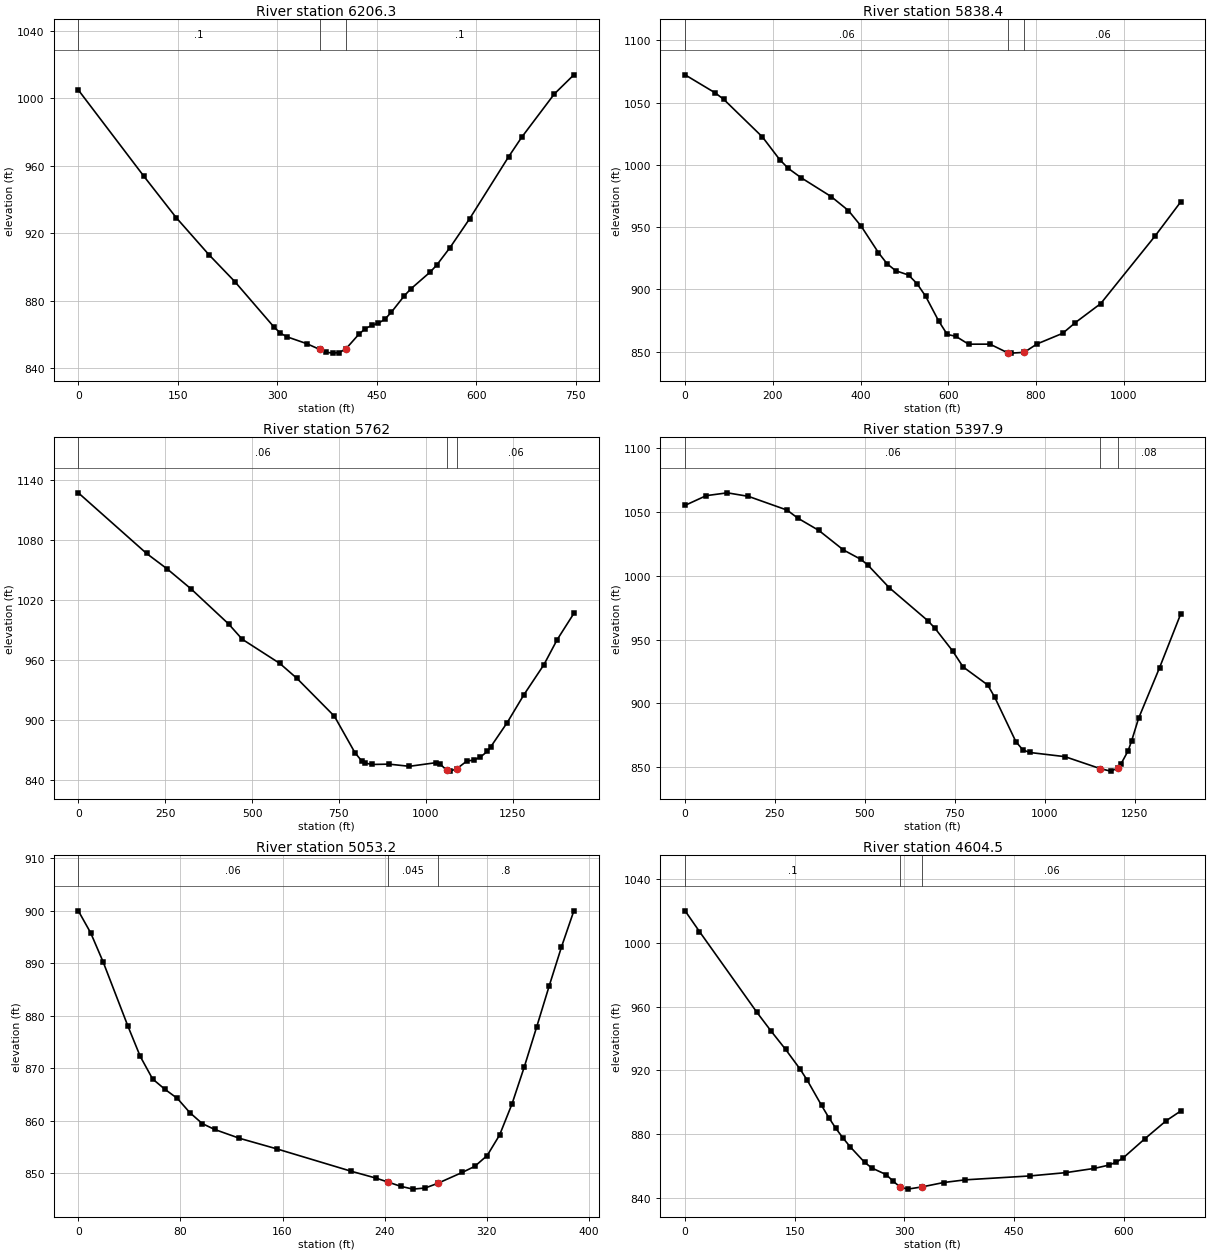
Type RM Length L Ch R = 1 ,6206.3  ,379.8,368,355.8
XS GIS Cut Line= 2
     1641300.228      279020.634     1641684.149      279661.465
#Sta/Elev= 30
       0 1004.92    98.3  954.03   147.4   929.3   196.6  907.37   235.9   891.3
   294.9  864.39   304.7  860.72   314.5  858.58     344  854.56   363.7  851.13
   373.5  849.46   383.4   848.9   393.2  849.25     403  851.28   422.7     860
   432.5  863.41   442.3  865.36   452.2  866.61     462  868.98   471.8  873.12
   491.5  882.94   501.3     887   530.8   897.1   540.6  901.28   560.3  911.46
   589.8  928.52   648.7  965.35   668.4   976.9   717.6 1002.57     747 1013.89
#Mann= 3 , 0 , 0
       0      .1       0   363.7    .045       0     403      .1       0
Bank Sta=363.7,403
XS Rating Curve= 0 ,0
Exp/Cntr=0.3,0.1

Type RM Length L Ch R = 1 ,5838.4  ,75.1,76.3,77.8
XS GIS Cut Line= 4
     1641169.897      278844.346     1641040.432      279427.649
     1641280.021      279577.753     1641303.114      279826.003
#Sta/Elev= 30
       0 1072.42    68.6 1057.92    88.2 1052.69   176.3  1022.5   215.5 1004.37
   235.1  997.29   264.5  989.76     333   974.6   372.2  963.41   401.6  950.71
   440.8  929.54   460.4  920.65     480  915.06   509.3   911.6   528.9  904.57
   548.5  894.43   577.9  874.75   597.5  863.88     617  862.38   646.2  856.04
     695  856.06   735.6  849.08   743.7  848.85     773  849.48   802.2  856.22
   860.7  864.77   889.8  873.43   947.4  888.64    1072  943.24  1129.6  970.26
#Mann= 3 , 0 , 0
       0     .06       0   735.6    .045       0     773     .06       0
Bank Sta=735.6,773
XS Rating Curve= 0 ,0
Exp/Cntr=0.3,0.1

Type RM Length L Ch R = 1 ,5762    ,346.8,364.2,381.6
XS GIS Cut Line= 4
     1641149.443      278585.943     1640956.719      279459.402
     1641196.309      279609.506     1641219.402      279857.756
#Sta/Elev= 30
       0 1127.61   196.6 1066.93   255.6 1051.55   324.4 1031.55   432.5  996.48
   471.8  981.17   579.9     957   629.1   942.1   737.2  904.15   796.2  867.73
   815.8   859.4   825.7  857.32   845.3  855.91   894.5  856.22     953  854.06
    1031  857.76  1040.7  856.65  1060.2  850.14    1070  849.24  1089.4  851.59
  1118.7   859.4  1138.2  860.22  1157.7  863.37  1177.2  868.93  1186.8  873.32
  1234.7  897.83  1282.7  925.64  1340.2  955.66  1378.6  980.83  1426.5    1007
#Mann= 3 , 0 , 0
       0     .06       0  1060.2    .045       0  1089.4     .06       0
Bank Sta=1060.2,1089.4
XS Rating Curve= 0 ,0
Exp/Cntr=0.3,0.1

Type RM Length L Ch R = 1 ,5397.9  ,341.4,344.7,347.9
XS GIS Cut Line= 3
     1639974.964      278898.443     1640721.164      279436.263
     1640831.295      279881.035
#Sta/Elev= 30
       0 1055.38    58.7 1062.99   117.4 1065.21   176.1 1062.44   283.8 1051.64
   313.1  1045.4   371.8 1035.72   440.3 1020.38   489.3 1012.93   508.8 1008.36
   567.6  990.79   675.2  964.81   694.8  958.93   743.7  941.23     773   928.6
   841.5  914.43   861.1  904.77   919.8  869.99   939.3  863.44   958.8  861.44
  1056.3  858.18  1153.8  848.84    1183  846.82  1202.5  849.01  1212.3  852.56
  1231.8  862.69  1241.5  870.39    1261  888.22  1319.5  928.08    1378     970
#Mann= 3 , 0 , 0
       0     .06       0  1153.8    .045       0  1202.5     .08       0
Bank Sta=1153.8,1202.5
XS Rating Curve= 0 ,0
Exp/Cntr=0.3,0.1

Type RM Length L Ch R = 1 ,5053.2  ,481,448.7,416.4
XS GIS Cut Line= 2
     1640420.525      279452.984     1640459.895      279839.215
#Sta/Elev= 30
       0     900     9.7  895.79    19.4  890.28    38.8  878.04    48.5  872.24
    58.2  867.93    67.9  865.95    77.6  864.22    87.4   861.5    97.1  859.42
   106.8   858.3   126.2  856.62   155.3  854.61   213.5  850.35   232.9  849.04
   242.7  848.26   252.4  847.47   262.1  846.92   271.8  847.14   281.5  848.02
   300.9  850.12   310.6  851.27   320.3  853.33     330  857.23   339.7  863.14
   349.4  870.26   359.1  877.88   368.8  885.62   378.5  893.11   388.2     900
#Mann= 3 , 0 , 0
       0     .06       0   242.7    .045       0   281.5      .8       0
Bank Sta=242.7,281.5
XS Rating Curve= 0 ,0
Exp/Cntr=0.3,0.1

Type RM Length L Ch R = 1 ,4604.5  ,389.4,369.2,349
XS GIS Cut Line= 2
     1639734.677      279795.065     1640410.957      279845.463
#Sta/Elev= 30
       0    1020    19.7 1006.99    98.3  956.35   117.9  944.46   137.6  933.08
   157.2  920.86   167.1  913.84   186.7  898.03   196.6   890.4   206.4  883.54
   216.2  877.49     226  872.01   245.7  862.29   255.5  858.77   275.2  854.59
     285  850.38   294.5  846.76   304.7   845.5   324.3   846.9   353.8  849.64
   383.3  851.32   471.8  853.77   520.9  855.83   560.2  858.51   579.9  860.56
   589.7  862.31   599.5  865.05     629  876.99   658.5  888.41   678.2  894.45
#Mann= 3 , 0 , 0
       0      .1       0   294.5    .045       0   324.3     .06       0
Bank Sta=294.5,324.3
XS Rating Curve= 0 ,0
Exp/Cntr=0.3,0.1

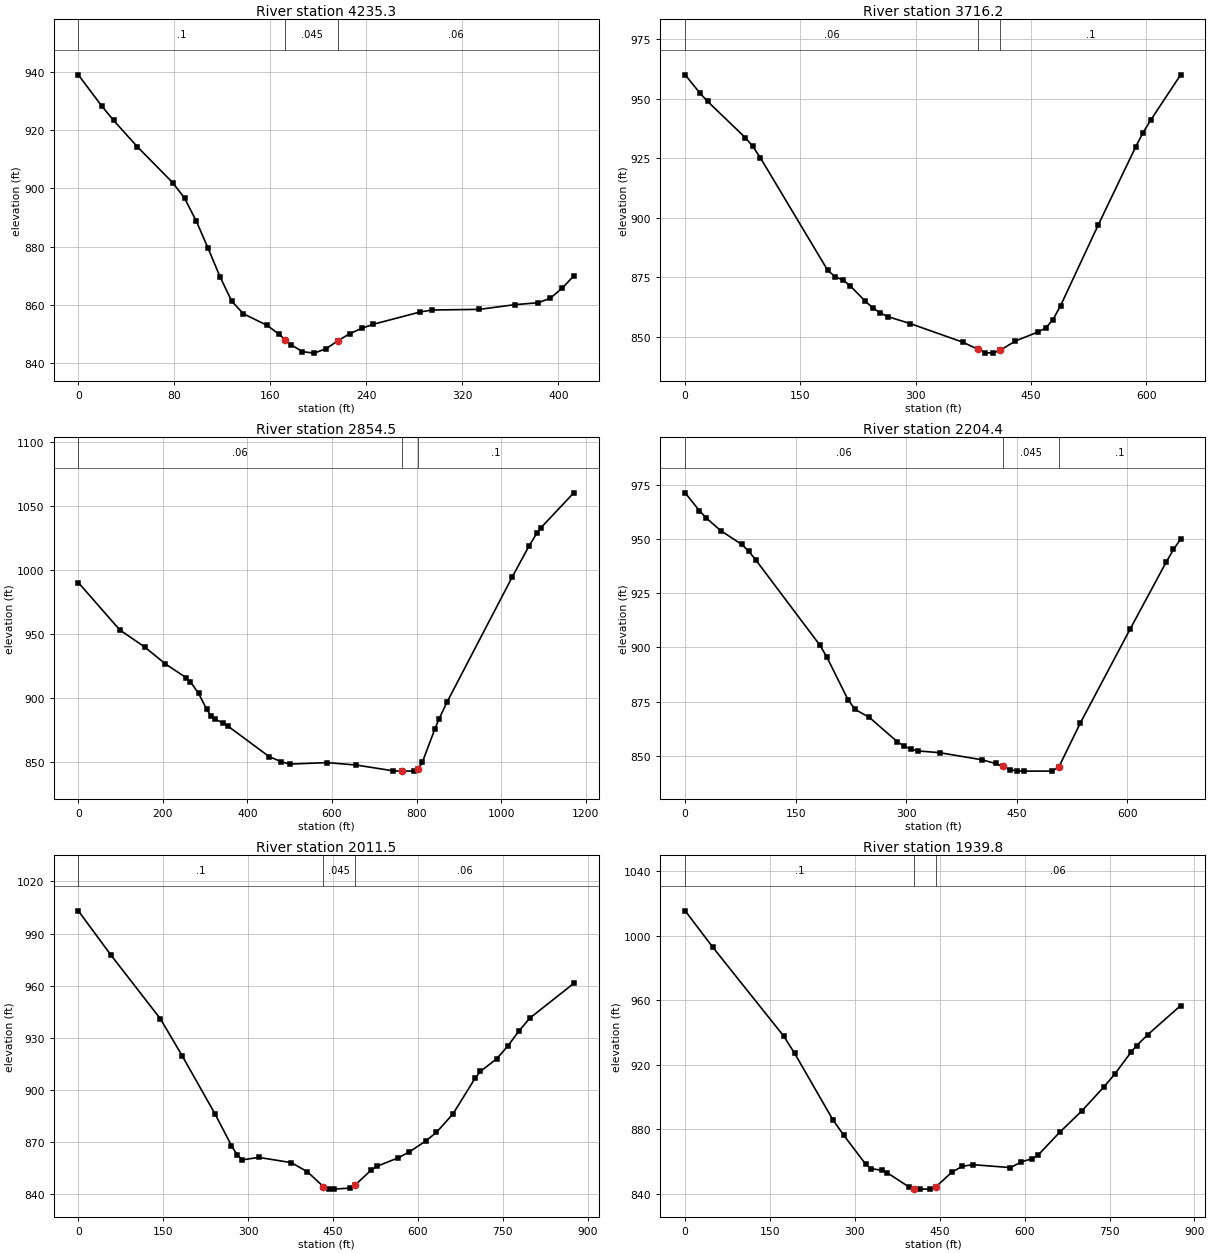
Type RM Length L Ch R = 1 ,4235.3  ,516.6,519,521.5
XS GIS Cut Line= 2
     1640103.595      280232.645     1640384.267      279929.747
#Sta/Elev= 30
       0  938.89    19.7   928.1    29.5  923.24    49.2  914.23    78.7  901.91
    88.5  896.65    98.3  888.78   108.2   879.4     118  869.76   127.8  861.32
   137.6  856.98   157.3  853.03   167.1  850.02   172.4  848.11     177  846.45
   186.8     844   196.6   843.5   206.5  845.02   216.3  847.73   226.1  850.14
     236  851.97   245.8  853.39   285.1  857.63     295  858.28   334.3   858.5
   363.8  860.11   383.4  860.78   393.3  862.32   403.1  865.71   412.9  869.98
#Mann= 3 , 0 , 0
       0      .1       0   172.4    .045       0   216.3     .06       0
Bank Sta=172.4,216.3
XS Rating Curve= 0 ,0
Exp/Cntr=0.3,0.1

Type RM Length L Ch R = 1 ,3716.2  ,839.4,861.8,884.1
XS GIS Cut Line= 2
     1640341.786      280667.558     1640827.984      280243.895
#Sta/Elev= 30
       0     960    19.5  952.21    29.3  948.81    78.2  933.67    87.9  930.02
    97.7  925.28   185.6  877.92   195.4  875.22   205.2   873.9     215  871.39
   234.5  864.98   244.3   862.2     254  860.06   263.8  858.54   293.1   855.6
   361.5  847.79   381.1  844.83   390.8  843.44   400.6  843.22   410.4  844.49
   429.9  848.32   459.2  852.09     469  853.69   478.8  857.32   488.6  863.12
   537.4  896.85   586.3  929.72     596  935.76   605.8  940.94   644.9     960
#Mann= 3 , 0 , 0
       0     .06       0   381.1    .045       0   410.4      .1       0
Bank Sta=381.1,410.4
XS Rating Curve= 0 ,0
Exp/Cntr=0.3,0.1

Type RM Length L Ch R = 1 ,2854.5  ,630.4,650.1,669.8
XS GIS Cut Line= 3
      1640362.24      280858.814     1641146.428      281077.013
     1641504.076      281093.376
#Sta/Elev= 30
       0  989.99    98.1  953.04   156.9  939.76     206  926.53     255  915.82
   264.8  912.76   284.4  903.56     304  890.98   313.8  885.96   323.6  883.25
   343.2  880.47     353  878.26   451.1  854.28   480.5  850.17   500.2   848.4
   588.4  849.54   657.1  847.66   745.3  843.12   764.9   842.9   794.4  842.99
   804.2  844.44     814  850.03     843   875.4   852.7  883.22     872  896.62
  1026.9  994.66  1065.6 1018.18  1084.9  1028.7  1094.6 1032.86    1172    1060
#Mann= 3 , 0 , 0
       0     .06       0   764.9    .045       0   804.2      .1       0
Bank Sta=764.9,804.2
XS Rating Curve= 0 ,0
Exp/Cntr=0.3,0.1

Type RM Length L Ch R = 1 ,2204.4  ,178,192.8,207.7
XS GIS Cut Line= 4
      1640323.25      280973.376     1640490.932      281145.607
     1640609.148      281405.847     1640630.738      281550.535
#Sta/Elev= 30
       0  971.32    19.2   963.1    28.8  959.66    48.1  953.89    76.9  947.48
    86.5  944.27    96.2  940.19   182.7  901.08   192.3   895.5   221.2  875.74
   230.8  871.34   249.9  867.71     288  856.43   297.5   854.4   307.1  852.96
   316.6   852.2   345.2  851.43   402.4  848.15   421.4  846.43   430.9  845.07
   440.5   843.6     450  842.97   459.5   842.9   497.6  842.92   507.2  844.81
     536  864.88   604.2  908.61     653  939.44   662.8  945.18   672.5     950
#Mann= 3 , 0 , 0
       0     .06       0   430.9    .045       0   507.2      .1       0
Bank Sta=430.9,507.2
XS Rating Curve= 0 ,0
Exp/Cntr=0.3,0.1

Type RM Length L Ch R = 1 ,2011.5  ,71.8,71.7,71.7
XS GIS Cut Line= 4
     1640191.689      281013.722     1640421.482      281275.089
     1640370.612      281496.111     1640663.553      281564.522
#Sta/Elev= 30
       0 1003.06      58  977.45     145  940.95   183.7  919.55   241.7  886.12
   270.7  867.92   280.4  862.74     290  859.75     319  861.16   376.4  858.15
   404.7  852.92   433.1  844.35   442.5  843.13     452   842.9   480.3  843.52
   489.8  845.44   518.1  854.01   527.6  856.02   565.4  860.92   584.5  864.23
   613.6   870.5     633   875.6   662.2  886.22     701  906.61   710.7  910.67
   739.8  918.04   759.2  925.32   778.6  933.86     798  941.34   875.6  961.31
#Mann= 3 , 0 , 0
       0      .1       0   433.1    .045       0   489.8     .06       0
Bank Sta=433.1,489.8
XS Rating Curve= 0 ,0
Exp/Cntr=0.3,0.1

Type RM Length L Ch R = 1 ,1939.8  ,373.4,336.3,299.2
XS GIS Cut Line= 4
     1640112.753      281041.788     1640342.546      281303.155
     1640291.675      281524.177     1640584.617      281592.588
#Sta/Elev= 30
       0 1015.36    48.3  993.02     174  937.78   193.3  927.12     261  885.89
   280.4  876.19     319  858.33   328.7  855.56     348  854.58   357.5  852.96
   395.3  844.26   404.7  843.09   414.2   842.9   433.1  842.92   442.5  844.17
   470.9  853.27   489.8  857.06   508.7  858.05   574.8  856.24   594.2  859.79
   613.6   861.8   623.3  863.85   662.2  878.27     701  891.38   739.8  906.18
   759.2  914.19   788.3  927.92     798   931.9   817.4  938.59   875.6  956.65
#Mann= 3 , 0 , 0
       0      .1       0   404.7    .045       0   442.5     .06       0
Bank Sta=404.7,442.5
XS Rating Curve= 0 ,0
Exp/Cntr=0.3,0.1

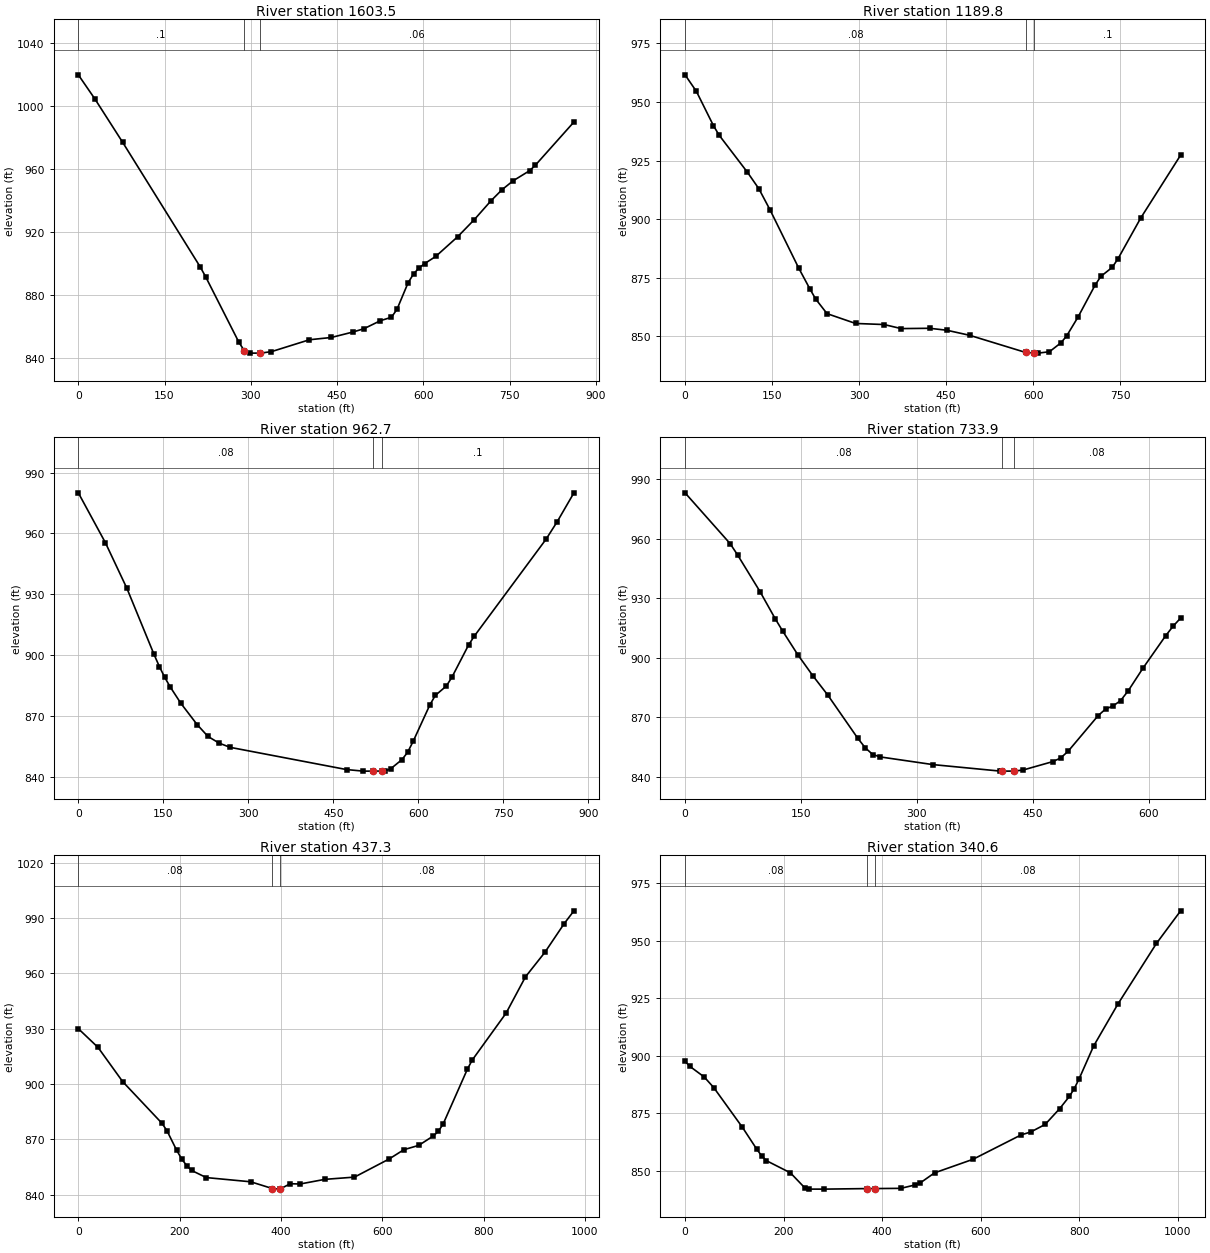
Type RM Length L Ch R = 1 ,1603.5  ,430.6,413.7,396.6
XS GIS Cut Line= 4
     1639797.257      281504.445     1640068.608      281569.106
     1640292.574      281607.264     1640645.282       281653.66
#Sta/Elev= 30
       0 1019.99    28.9  1004.6      77  977.11   211.6     898   221.2  891.66
     279  849.99   288.4  844.57   297.9   842.9   316.8  842.91   335.8  843.84
     402  851.42   439.9  852.85   477.7  856.34   496.7  858.43   525.4  863.55
   544.6  865.73   554.2  870.77   573.4  887.58   583.1  893.37   592.7  897.14
   602.3  899.88   621.5   904.4     660  917.06   688.8  927.91   717.7  939.86
   736.9   946.9   756.1  952.55     785  959.02   794.6  962.38   861.9  989.97
#Mann= 3 , 0 , 0
       0      .1       0   288.4    .045       0   316.8     .06       0
Bank Sta=288.4,316.8
XS Rating Curve= 0 ,0
Exp/Cntr=0.3,0.1

Type RM Length L Ch R = 1 ,1189.8  ,228.3,227.1,226.1
XS GIS Cut Line= 3
     1639917.831      282289.936     1639975.123      282052.089
     1640495.956      281736.117
#Sta/Elev= 30
       0  961.56    19.6  954.49    48.9  939.91    58.7  935.83   107.6  919.98
   127.2  912.98   146.8  903.81   195.7  879.22   215.3  870.18   225.1  865.95
   244.6  859.74   293.8  855.55   342.9  855.09   372.4  853.36   421.5  853.49
     451  852.66   490.3   850.5   586.8  843.19   601.8  842.91   608.2   842.9
   627.8  843.49   647.5  847.28   657.3  850.18     677  858.27   706.4  871.89
   716.3  875.61   735.9  879.46   745.8   883.1   785.1  900.53   853.8  927.33
#Mann= 3 , 0 , 0
       0     .08       0   586.8    .045       0   601.8      .1       0
Bank Sta=586.8,601.8
XS Rating Curve= 0 ,0
Exp/Cntr=0.3,0.1

Type RM Length L Ch R = 1 ,962.7   ,230.9,228.7,226.5
XS GIS Cut Line= 3
     1640050.983      282408.675     1640168.532      282212.387
     1640705.955      281854.156
#Sta/Elev= 30
       0     980    47.7  955.48    85.8  932.91   133.5  900.48     143  894.44
   152.5   889.1   162.1  884.41   181.1  876.26   209.7  865.82   228.8     860
   248.4  856.71   267.9  854.62   473.4  843.67   502.8   842.9   520.1   842.9
   535.1  842.91   541.9  842.95   551.7  844.14   571.3   848.6   581.1  852.15
   590.9  857.53   620.2  875.38     630  880.18   649.6  884.84   659.4  889.18
   688.7  904.99   698.5  909.26   825.7  957.22   845.3  965.82   874.7     980
#Mann= 3 , 0 , 0
       0     .08       0   520.1    .045       0   535.1      .1       0
Bank Sta=520.1,535.1
XS Rating Curve= 0 ,0
Exp/Cntr=0.3,0.1

Type RM Length L Ch R = 1 ,733.9   ,303.4,296.6,289.6
XS GIS Cut Line= 2
     1640226.772      282497.726     1640722.637      282091.347
#Sta/Elev= 30
       0  983.09    58.3  957.51      68  951.79    97.1  933.26   116.6   919.7
   126.3  913.45   145.7  901.63   165.1  891.07   184.6  881.24   223.4  859.48
   233.1  854.67   242.8  851.27   252.6  850.05   320.6  846.19     408   842.9
   410.4   842.9   425.4  842.92   437.1  843.44     476  847.73   485.7  849.48
   495.4  852.84   534.3  870.82     544  874.18   553.7  875.74   563.4  878.42
   573.1  883.25   592.5  894.85   621.7  911.08   631.4  915.93   641.1  920.01
#Mann= 3 , 0 , 0
       0     .08       0   410.4    .045       0   425.4     .08       0
Bank Sta=410.4,425.4
XS Rating Curve= 0 ,0
Exp/Cntr=0.3,0.1

Type RM Length L Ch R = 1 ,437.3   ,96.7,96.8,96.8
XS GIS Cut Line= 4
     1640373.945      282583.096     1640646.012       282580.17
     1640877.444      282230.427      1640823.18      281948.679
#Sta/Elev= 30
       0  930.02    38.9  919.85    87.5   901.3   165.2  878.64   174.9  874.68
   194.3  863.93   204.1  859.32   213.8  855.71   223.5  853.09   252.6   849.2
   340.4  846.91   382.8  843.27   397.8  842.93   418.4  845.85   437.9  845.72
   486.6  848.23   545.2  849.45   613.4  859.26   642.7  864.33     672  866.67
     701  871.82   710.6  874.24   720.2  878.26     768  907.98   777.5  912.92
   844.5  938.45   882.8  958.16     921  971.42   959.3  987.07   978.4  993.97
#Mann= 3 , 0 , 0
       0     .08       0   382.8    .045       0   397.8     .08       0
Bank Sta=382.8,397.8
XS Rating Curve= 0 ,0
Exp/Cntr=0.3,0.1

Type RM Length L Ch R = 1 ,340.6   ,82.2,90.8,99.6
XS GIS Cut Line= 4
     1640449.373      282640.983      1640721.44      282638.057
     1640974.621      282255.447     1641249.437      282245.129
#Sta/Elev= 30
       0  897.67     9.7   895.5    38.9  890.87    58.3  886.26   116.6  868.94
   145.8   859.4   155.5  856.58   165.2  854.49   213.8  849.21   242.9  842.71
   252.6  842.13   281.8  842.12   370.2  842.36   385.2  842.36     438  842.46
   467.3  843.96   477.1  844.78   506.4  849.19   584.4  855.08   682.1  865.69
   701.6  866.95   730.9  870.24   760.3  877.08     780   882.4   789.8  885.73
   799.6  889.94   829.1  904.24   878.2  922.44   956.8  948.92  1005.9  963.09
#Mann= 3 , 0 , 0
       0     .08       0   370.2    .045       0   385.2     .08       0
Bank Sta=370.2,385.2
XS Rating Curve= 0 ,0
Exp/Cntr=0.3,0.1

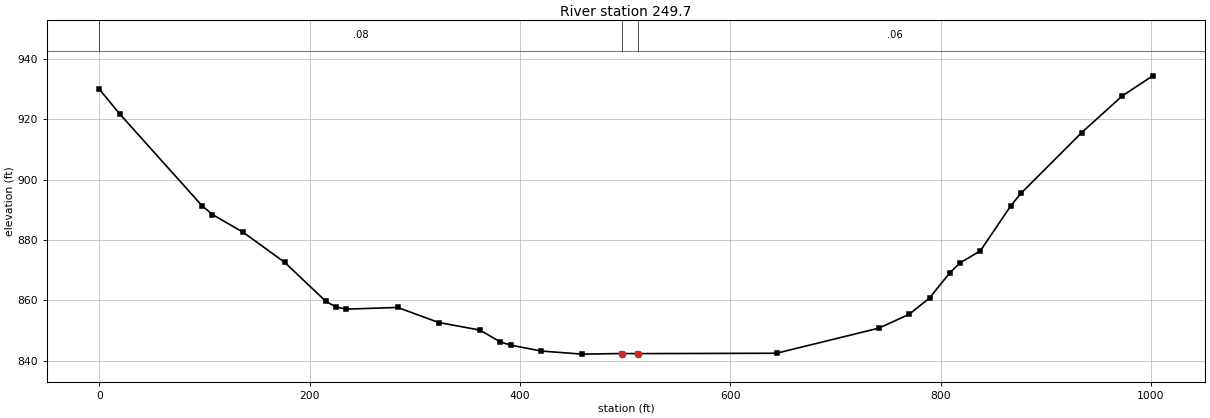
Type RM Length L Ch R = 1 ,249.7   ,217.7,249.7,281.8
XS GIS Cut Line= 4
     1640354.299      282646.691     1640711.863      282703.057
     1641024.629      282488.491     1641155.897       282263.47
#Sta/Elev= 30
       0     930    19.6   921.7    97.8   891.3   107.6  888.44     137  882.49
   176.1  872.62   215.2  859.72     225  857.76   234.8  857.06   283.7  857.62
   322.8  852.62     362  850.11   381.4  846.16   391.2  845.13   420.3  843.16
   459.2  842.14   497.1  842.34   512.1  842.31     644  842.43   741.3  850.76
   770.2  855.35   789.5  860.77   808.8   869.1   818.5  872.39   837.8  876.37
   866.7  891.26   876.4  895.44   934.2   915.6   972.8  927.77  1001.8  934.43
#Mann= 3 , 0 , 0
       0     .08       0   497.1    .045       0   512.1     .06       0
Bank Sta=497.1,512.1
XS Rating Curve= 0 ,0
Exp/Cntr=0.3,0.1

Chan Stop Cuts=-1
Use User Specified Reach Order=0
Composite Channel Slope=5